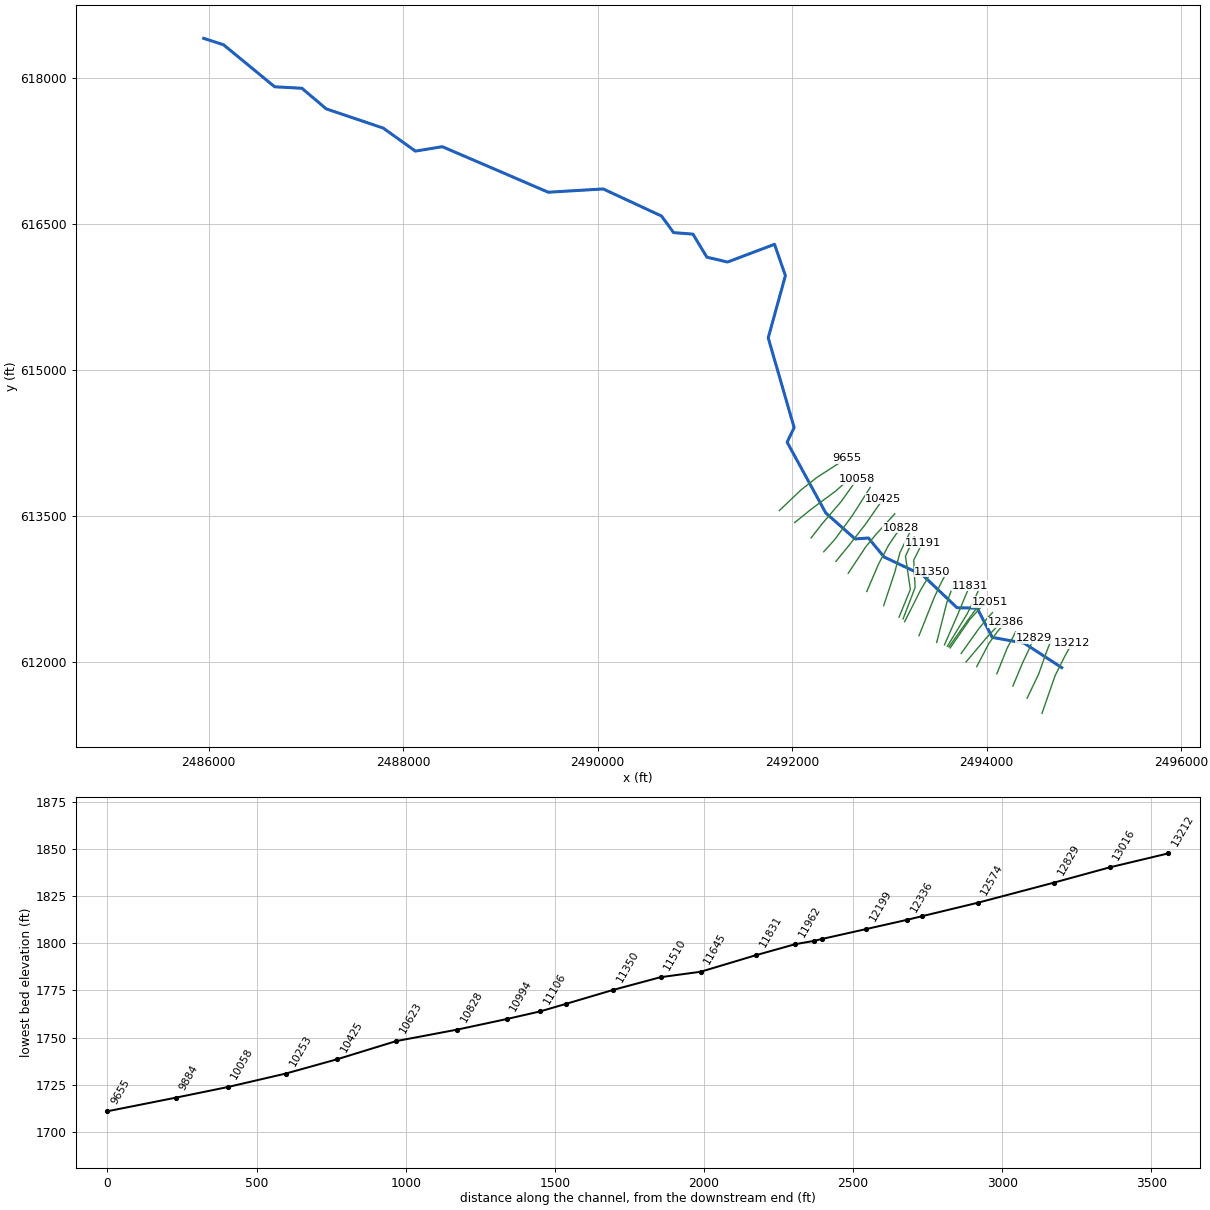
--- DICERN.prj (project) ---

Proj Title=DICERN
Current Plan=p01
Default Exp/Contr=0,0
English Units
Geom File=g01
Flow File=f01
Plan File=p01
BEGIN DESCRIPTION:
Stream Name: Dice Run
Flood Zone: Zone A
Pendleton County, WV
WVDHSEM Flood Warning & Analysis Mapping
HEC-RAS Version: 5.0.7
Hydrology Method:
Regression was used
Model Notes:
Model ties in with South Fork South Branch South Potomac River
END DESCRIPTION:
DSS Export Rating Curves= 0
DSS Export Rating Curve Sorted= 0
DSS Export Volume Flow Curves= 0
DXF OffsetX= 0
DXF OffsetY= 0
DXF ScaleX= 0
DXF ScaleY= 0

--- DICERN.p01 (plan) ---

Plan Title=Floodplain
Program Version=5.07
Short Identifier=Floodplain
Geom File=g01
Flow File=f01
Subcritical Flow
K Sum by GR= 0
Std Step Tol= 0.01
Critical Tol= 0.01
Num of Std Step Trials= 20
Max Error Tol= 0.3
Flow Tol Ratio= 0.001
Split Flow NTrial= 30
Split Flow Tol= 0.02
Split Flow Ratio= 0.02
Log Output Level= 0
Friction Slope Method= 1
Unsteady Friction Slope Method= 2
Unsteady Bridges Friction Slope Method= 1
Parabolic Critical Depth
Global Vel Dist= 0 , 0 , 0
Global Log Level= 0
CheckData=True
Encroach Param=-1 ,0,0, 0
Mapping Interval=1HOUR
Computation Time Step Use Courant=        0
Computation Time Step Use Time Series=    0
Computation Time Step Count To Double=0
Computation Time Step Max Doubling=0
Computation Time Step Max Halving=0
Computation Time Step Residence Courant=0
Run HTab= 0
Run UNet= 0
Run Sediment= 0
Run PostProcess= 0
Run WQNet= 0
Run RASMapper= 0
UNET Theta= 0
UNET Theta Warmup= 0
UNET ZTol= 0
UNET ZSATol= 0
UNET MxIter= 0
UNET Max Iter WO Improvement= 0
UNET MaxInSteps= 0
UNET DtIC= 0
UNET DtMin= 0
UNET MaxCRTS= 0
UNET WFStab= 0
UNET SFStab= 0
UNET WFX= 1
UNET SFX= 1
UNET 1D Methodology=Finite Difference
UNET DSS MLevel= 1
UNET Pardiso=0
UNET DZMax Abort= 0
UNET Use Existing IB Tables= 0
UNET Froude Reduction=False
UNET Froude Limit= 0
UNET Froude Power= 0
UNET D1 Cores= 0
UNET D2 Coriolis=0
UNET D2 Cores= 0
UNET D2 Theta= 1
UNET D2 Theta Warmup= 1
UNET D2 Z Tol= 0.01
UNET D2 Volume Tol= 0.01
UNET D2 Max Iterations= 20
UNET D2 Equation= 0
UNET D2 RampUpFraction=0.1
UNET D2 TimeSlices= 1
UNET D2 BCVolumeCheck=0
UNET D1D2 MaxIter= 0
UNET D1D2 ZTol=0.01
UNET D1D2 QTol=0.1
UNET D1D2 MinQTol=1
Write IC File= 0
Write IC File at Fixed DateTime=0
Write IC File at Sim End=0
Echo Input=False
Echo Parameters=False
Echo Output=False
Write Detailed= 0
HDF Write Warmup=0
HDF Write Time Slices=0
HDF Flush=0
HDF Face Node Velocities=0
HDF Compression= 1
HDF Chunk Size= 1
HDF Spatial Parts= 1
HDF Use Max Rows=0
HDF Fixed Rows= 1
Calibration Method= 0
Calibration Iterations= 20
Calibration Max Change=0.05
Calibration Tolerance=0.2
Calibration Maximum=1.5
Calibration Minimum=0.5
Calibration Optimization Method= 1
WQ AD Non Conservative
WQ ULTIMATE=-1
WQ Max Comp Step=1HOUR
WQ Output Interval=15MIN
WQ Output Selected Increments= 0
WQ Output face flow=0
WQ Output face velocity=0
WQ Output face area=0
WQ Output face dispersion=0
WQ Output cell volume=0
WQ Output cell surface area=0
WQ Output cell continuity=0
WQ Output cumulative cell continuity=0
WQ Output face conc=0
WQ Output face dconc_dx=0
WQ Output face courant=0
WQ Output face peclet=0
WQ Output face adv mass=0
WQ Output face disp mass=0
WQ Output cell mass=0
WQ Output cell source sink temp=0
WQ Output nsm pathways=0
WQ Output nsm derived pathways=0
WQ Output MaxMinRange=-1
WQ Daily Max Min Mean=-1
WQ Daily Range=0
WQ Daily Time=0
WQ Create Restart=0
WQ Fixed Restart=0
WQ System Summary=0
WQ Write To DSS=0
WQ Use Fixed Temperature=0
Sorting and Armoring Iterations= 10
XS Update Threshold= 0.02
Bed Roughness Predictor= 0
Hydraulics Update Threshold= 0.02
Energy Slope Method= 1
Volume Change Method= 1
Sediment Retention Method= 0
XS Weighting Method= 0
Number of US Weighted Cross Sections= 1
Number of DS Weighted Cross Sections= 1
Upstream XS Weight=0
Main XS Weight=1
Downstream XS Weight=0
Number of DS XS's Weighted with US Boundary= 1
Upstream Boundary Weight= 1
Weight of XSs Associated with US Boundary= 0
Number of US XS's Weighted with DS Boundary= 1
Downstream Boundary Weight= 0.5
Weight of XSs Associated with DS Boundary= 0.5
Percentile Method= 0
Sediment Output Level= 3
Mass or Volume Output= 0
Output Increment Type= 1
Profile and TS Output Increment= 1
XS Output Flag= 0
XS Output Increment= 10
Write Gradation File= 0
Read Gradation Hotstart= 0
Write HDF5 File= 1
Write Binary Output= 1
Write DSS Sediment File= 0
SV Curve= 0
Specific Gage Flag= 0

--- DICERN.f01 (steady flow) ---

Flow Title=Flows
Program Version=5.07
Number of Profiles= 6
Profile Names=P100yr,P10yr,P25yr,P50yr,P500yr,P101yr
River Rch & RM=DICERN,Main            ,13212
     595     278     393     491     872     724
River Rch & RM=DICERN,Main            ,10623
     662     309     437     546     972     806
River Rch & RM=DICERN,Main            ,7977
     750     349     495     619    1102     913
Boundary for River Rch & Prof#=DICERN,Main            , 1
Up Type= 0
Dn Type= 3
Dn Slope=0.03208
Boundary for River Rch & Prof#=DICERN,Main            , 2
Up Type= 0
Dn Type= 3
Dn Slope=0.03208
Boundary for River Rch & Prof#=DICERN,Main            , 3
Up Type= 0
Dn Type= 3
Dn Slope=0.03208
Boundary for River Rch & Prof#=DICERN,Main            , 4
Up Type= 0
Dn Type= 3
Dn Slope=0.03208
Boundary for River Rch & Prof#=DICERN,Main            , 5
Up Type= 0
Dn Type= 3
Dn Slope=0.03208
Boundary for River Rch & Prof#=DICERN,Main            , 6
Up Type= 0
Dn Type= 3
Dn Slope=0.03208
DSS Import GetInterval= 0
DSS Import GetPeak= 0
DSS Import FillOption= 0

--- DICERN.g01 (geometry) ---

Geom Title=Geometry
Program Version=5.07

River Reach=DICERN          ,Main
Reach XY= 30
     2494772.346      611940.385     2494385.504      612192.346
     2494058.385      612251.554     2493902.099      612552.446
     2493695.499      612556.211     2493345.369      612889.632
     2492945.923      613078.022     2492784.821      613273.352
     2492647.809      613263.595     2492346.157      613530.827
      2491948.78      614259.032      2492020.85      614408.696
     2491754.505      615331.3862491931.07121676615970.975173943
2491819.27237866616293.0623027532491336.46544155616110.846188349
     2491123.838      616160.674     2490980.403      616397.465
     2490781.384      616413.492     2490657.556      616583.589
     2490058.016      616862.066     2489492.866      616828.471
     2488403.932      617296.812     2488126.512      617251.207
     2487796.052      617488.008     2487210.749      617685.376
     2486960.236      617897.112     2486679.969      617912.584
      2486154.69      618344.301     2485950.221      618410.676

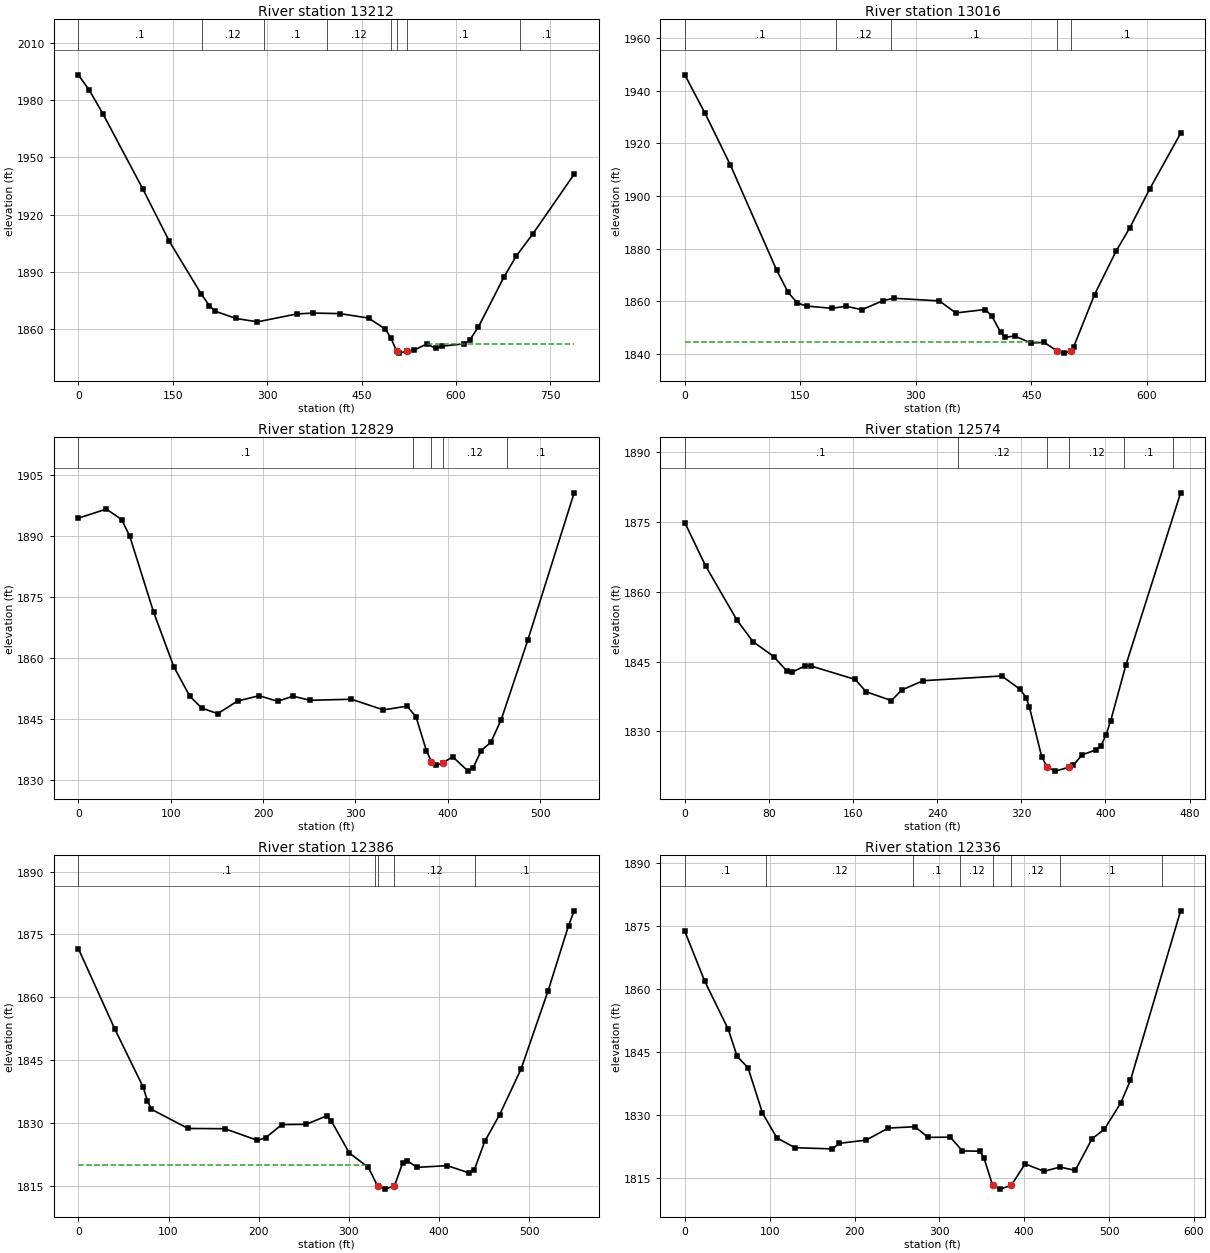
Type RM Length L Ch R = 1 ,13212   ,194.1,196.7,196.9
XS GIS Cut Line= 4
2494569.00925291611470.2434955982494704.42591956611859.132384509
2494798.17591956612046.6323844942494878.03703067612192.465717822
#Sta/Elev= 30
       0 1993.11    17.6 1984.99    38.8 1972.88   102.6 1933.36   144.7    1906
   195.5  1878.4   208.2 1872.51   216.7 1869.66   250.6 1865.76   284.5    1864
   347.4 1868.14   373.4 1868.59     416 1868.29     461 1865.97   487.9 1860.19
   496.5 1855.51  505.861848.706   509.9 1847.65  522.121848.705   533.3 1849.19
   553.5 1852.43     568 1850.14     577 1851.28   612.8 1852.51   621.7 1854.43
   635.4 1861.22   676.4 1887.56   695.7 1898.39   722.5 1910.16   787.7 1941.18
#Mann= 8 ,-1 , 0
       0      .1       0  195.98     .12       0  295.14      .1       0
  394.29     .12       0  496.12      .1       0  505.86    .045       0
  522.12      .1       0  701.94      .1       0
#XS Ineff= 1 ,-1
  553.58787.6912 1852.49
Permanent Ineff=
       F
Bank Sta=505.86,522.12
XS Rating Curve= 0 ,0
Exp/Cntr(USF)=0,0
Exp/Cntr=0.3,0.1

Type RM Length L Ch R = 1 ,13016   ,186.5,186.8,186.8
XS GIS Cut Line= 4
2494416.23147509611626.4934955982494534.28703067611873.021273389
2494624.56480846612126.4934956132494662.75925288612220.243495598
#Sta/Elev= 30
       0 1946.13    26.2 1931.54    59.2 1911.79   119.1  1871.9   134.1 1863.35
   146.1 1859.31   158.1 1858.14   191.1 1857.28   209.1 1858.07   230.1 1856.76
   257.1 1860.19     271 1861.11   330.5  1860.1   351.8 1855.52     390 1856.82
   398.5 1854.35   409.8 1848.27   415.4 1846.21   428.2 1846.76   449.4 1844.05
   466.4 1844.34  483.151841.082   491.9 1840.23  501.371841.081   504.6 1842.51
   531.9 1862.52   559.7 1878.98   577.4  1887.8   603.3  1902.6   643.6 1923.88
#Mann= 5 ,-1 , 0
       0      .1       0  196.91     .12       0  268.29      .1       0
  483.15    .045       0  501.37      .1       0
#XS Ineff= 2 , 0
          462.35 1844.44
Permanent Ineff=
       F       F
Bank Sta=483.15,501.37
XS Rating Curve= 0 ,0
Exp/Cntr(USF)=0,0
Exp/Cntr=0.3,0.1

Type RM Length L Ch R = 1 ,12829   ,254.4,255.1,251.6
XS GIS Cut Line= 4
2494270.39814177611751.4934956132494364.14814177611977.187940046
2494444.00925288612147.3268289572494482.20369732612244.549051151
#Sta/Elev= 30
       0 1894.38    30.4 1896.62      47 1894.02    55.7 1889.91    81.6 1871.19
   103.3 1857.87   120.6  1850.6   133.6 1847.66   150.9 1846.28   172.6 1849.41
   195.7 1850.69   215.9 1849.32   232.4 1850.59   250.7 1849.57   295.7 1849.83
   330.2 1847.21   355.9 1848.13   365.6 1845.49   376.9 1837.14   382.3 1834.46
   387.7 1833.55     395 1834.26   405.3 1835.66     422 1832.14   427.4 1832.94
   436.2 1837.21   446.5 1839.21   457.7 1844.72   486.6 1864.36   536.8 1900.62
#Mann= 5 ,-1 , 0
       0      .1       0  362.55     .12       0   382.3    .045       0
     395     .12       0  463.65      .1       0
Bank Sta=382.3,395
XS Rating Curve= 0 ,0
Exp/Cntr(USF)=0,0
Exp/Cntr=0.3,0.1

Type RM Length L Ch R = 1 ,12574   ,189.9,188.2,187.4
XS GIS Cut Line= 4
2494104.88888249611876.4934956132494210.79166028612140.382384509
 2494269.8194381612251.4934956132494295.86110476612307.049051151
#Sta/Elev= 30
       0 1874.88    19.8 1865.57    49.4    1854    64.8 1849.31    84.5 1846.11
    97.4 1842.91   101.7 1842.72   114.6  1844.1   120.1 1844.06   162.1 1841.18
   172.4 1838.53   196.5 1836.64   206.3 1838.92   226.7 1840.91   301.3 1841.93
   318.4 1839.14   324.6  1837.3   327.6 1835.33   339.4 1824.56  344.561822.361
   352.5 1821.48  365.74 1822.36   369.5 1822.76   377.8 1824.98   391.4 1826.08
   395.9 1826.98   400.4  1829.2     405 1832.31   419.4 1844.24   471.5 1881.28
#Mann= 6 ,-1 , 0
       0      .1       0  259.37     .12       0  344.56    .045       0
  365.74     .12       0  417.94      .1       0  464.21     .12       0
Bank Sta=344.56,365.74
XS Rating Curve= 0 ,0
Exp/Cntr(USF)=0,0
Exp/Cntr=0.5,0.3

Type RM Length L Ch R = 1 ,12386   ,50.2,49.2,48.4
XS GIS Cut Line= 4
2493898.29166028611951.1462733752494025.02777138612192.465717822
2494117.04166028612319.2018289272494198.63888255612407.743495613
#Sta/Elev= 30
       0 1871.65    40.4 1852.47      72 1838.56    76.5 1835.37      81 1833.33
   121.6 1828.76   162.4  1828.7   198.5 1825.93   207.5 1826.53   225.6 1829.68
   252.7 1829.75   275.5 1831.78   280.5 1830.51   300.3 1822.93   321.4 1819.49
  331.641815.078   339.8  1814.3  350.451815.076   359.6 1820.64     364  1821.1
   375.8 1819.49     409  1819.9     433 1818.16   438.7 1818.77   450.5 1825.68
     467 1832.04   490.7 1842.91   520.8 1861.63   543.4 1877.12   549.6 1880.63
#Mann= 5 ,-1 , 0
       0      .1       0  329.03     .12       0  331.64    .045       0
  350.45     .12       0  439.32      .1       0
#XS Ineff= 2 ,-1
       0     321 1819.96     360549.5976 1819.96
Permanent Ineff=
       F       F
Bank Sta=331.64,350.45
XS Rating Curve= 0 ,0
Exp/Cntr(USF)=0,0
Exp/Cntr=0.5,0.3

Type RM Length L Ch R = 1 ,12336   ,136.7,137.2,136.2
XS GIS Cut Line= 4
2493788.91666031611999.7573844942493986.83332697612234.132384509
2494090.99999362612346.979606718 2494177.8055492612435.521273389
#Sta/Elev= 30
       0 1873.84    23.4 1861.99    51.2  1850.5    61.7 1844.04    74.5 1841.34
    91.5 1830.56   108.5 1824.63   129.8 1822.29   173.8    1822   182.3 1823.34
   213.6 1824.09   239.7 1826.96   271.1 1827.29   286.8 1824.75   312.9  1824.8
   327.1 1821.53   347.9 1821.45   352.5 1819.86  362.781813.326   371.5 1812.42
  384.771813.327     401 1818.43   423.3 1816.67   442.3 1817.68   460.1 1816.88
   479.9 1824.43   494.3 1826.64   513.8 1832.97   525.2 1838.36   584.3 1878.72
#Mann= 8 ,-1 , 0
       0      .1       0   95.81     .12       0  269.34      .1       0
  324.73     .12       0  362.78    .045       0  384.77     .12       0
  442.22      .1       0   561.8     .12       0
Bank Sta=362.78,384.77
XS Rating Curve= 0 ,0
Exp/Cntr(USF)=0,0
Exp/Cntr=0.5,0.3

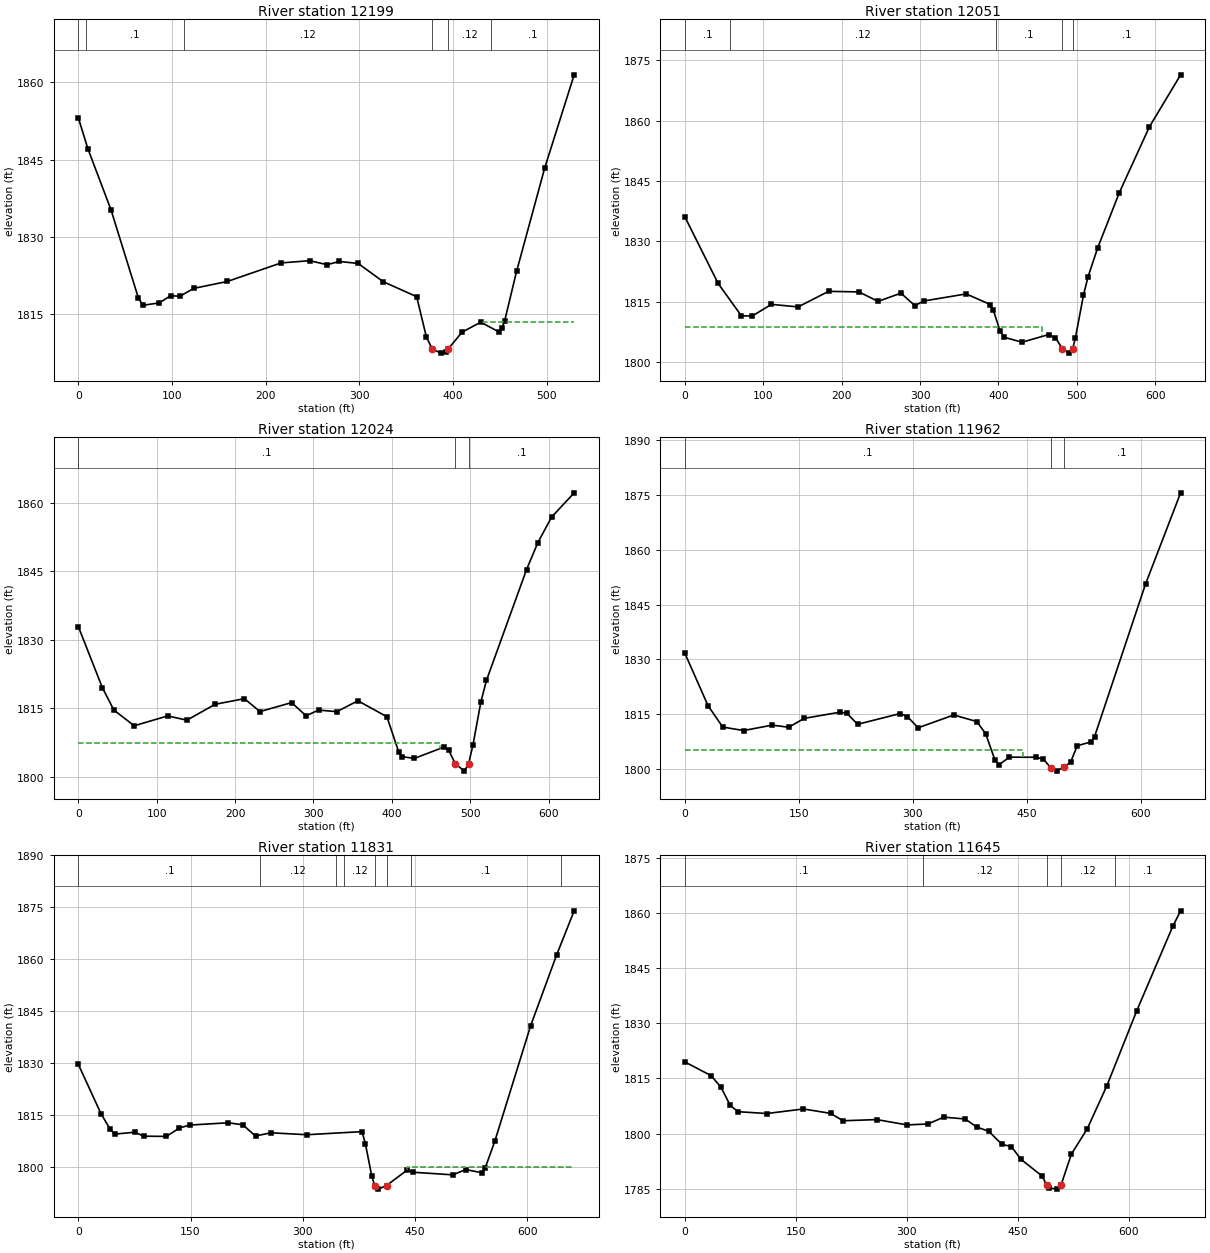
Type RM Length L Ch R = 1 ,12199   ,148.6,148,145.3
XS GIS Cut Line= 4
 2493738.5694381612086.5629400462493913.91666031612333.090717837
2494000.72221583612440.7296067332494059.74999365612506.701828942
#Sta/Elev= 30
       0 1853.14    10.2 1847.13    34.8 1835.34    64.2 1818.14    69.1 1816.79
    86.4 1817.25    98.6 1818.65   108.4 1818.53   123.1 1820.06     159  1821.4
   216.4    1825     247 1825.43   265.5 1824.66   278.6 1825.28   298.7  1824.9
   325.4 1821.37   361.2 1818.45   371.6  1810.6  377.781808.357   386.7 1807.51
   392.6 1807.64  394.991808.359   409.6 1811.57   429.6 1813.51   449.1 1811.61
   452.3 1812.39   455.1 1813.76   467.8 1823.34   497.8 1843.37   529.3 1861.47
#Mann= 6 ,-1 , 0
       0     .12       0    8.06      .1       0  113.28     .12       0
  377.78    .045       0  394.99     .12       0  440.99      .1       0
#XS Ineff= 2 , 0
                           432.1         1813.56
Permanent Ineff=
       F       F
Bank Sta=377.78,394.99
XS Rating Curve= 0 ,0
Exp/Cntr(USF)=0,0
Exp/Cntr=0.3,0.1

Type RM Length L Ch R = 1 ,12051   ,25.5,26.6,27
XS GIS Cut Line= 4
2493625.72221586612143.8546067182493825.37499362 612433.78516227
2493950.37499362612570.9379400462494033.70832697612616.076828942
#Sta/Elev= 30
       0 1836.16    42.5 1819.58    72.3  1811.5    86.3 1811.53   110.5 1814.38
   144.5 1813.75   183.4 1817.62   222.2 1817.47   246.5 1815.12   275.7 1817.17
   293.4 1814.07   304.9 1815.22   358.9 1816.98   389.7 1814.34   393.4 1813.02
   402.2  1807.7   407.5  1806.2   430.2 1804.98   464.2 1806.89   472.8 1806.11
  481.481803.379   489.7 1802.27  494.75 1803.38   498.2 1806.04   508.5  1816.7
   514.4  1821.3   526.7 1828.46   554.3 1842.17   592.6 1858.49   632.4  1871.4
#Mann= 5 ,-1 , 0
       0      .1       0   57.96     .12       0  396.96      .1       0
  481.48    .045       0  494.75      .1       0
#XS Ineff= 2 , 0
          455.96 1808.73
Permanent Ineff=
       F       F
Bank Sta=481.48,494.75
XS Rating Curve= 0 ,0
Exp/Cntr(USF)=0,0
Exp/Cntr=0.3,0.1

Type RM Length L Ch R = 1 ,12024   ,60.6,62.6,63.7
XS GIS Cut Line= 4
2493612.28319703612153.9475015832493835.85692014612468.909023921
2493930.50856934612595.3832103512494008.02500618612637.813259993
#Sta/Elev= 30
       0 1832.87    30.6 1819.53    45.3 1814.62    71.3 1811.17     114 1813.33
   138.5  1812.4   174.6 1815.88   211.9  1817.1   231.7 1814.28   272.1 1816.24
   290.6 1813.36   306.5 1814.61   329.8 1814.26   356.7 1816.64   393.7 1813.15
   408.7  1805.5   412.6 1804.43   428.7 1804.03   466.9 1806.54   472.6 1805.79
     481 1802.86   492.6 1801.25   497.9 1802.84   503.6 1807.07   513.6  1816.4
   520.7  1821.1   571.8 1845.33   586.3 1851.25   603.8 1856.83   632.6 1862.14
#Mann= 3 , 0 , 0
       0      .1       0     481    .045       0   497.9      .1       0
#XS Ineff= 2 , 0
          461.17 1807.37
Permanent Ineff=
       F       F
Bank Sta=481,497.9
XS Rating Curve= 0 ,0
Exp/Cntr(USF)=0,0
Exp/Cntr=0.3,0.1

Type RM Length L Ch R = 1 ,11962   ,130.1,130.9,131.8
XS GIS Cut Line= 4
2493596.75978272 612160.817207232493800.17923225612494.219481911
 2493871.4127579612637.4208994512493914.00600004612729.951046168
#Sta/Elev= 30
       0 1831.74    30.5 1817.42    49.9 1811.55    77.4  1810.6   114.9 1812.08
   136.8  1811.5   157.2 1813.93   203.9  1815.6   213.3 1815.32   227.3  1812.3
   283.6 1815.25   292.9 1814.41     307 1811.35   353.9 1814.85   384.2 1813.05
   395.8 1809.77   407.9 1802.65   413.6 1801.27     427 1803.33   461.6 1803.31
   471.7 1802.82   481.3  1800.5   489.6 1799.52   498.5 1800.66   507.5  1801.9
   516.4 1806.46   534.3 1807.48   539.2 1808.97   606.3 1850.64   652.4  1875.5
#Mann= 3 , 0 , 0
       0      .1       0   481.3    .045       0   498.5      .1       0
#XS Ineff= 2 , 0
          444.67 1805.34
Permanent Ineff=
       F       F
Bank Sta=481.3,498.5
XS Rating Curve= 0 ,0
Exp/Cntr(USF)=0,0
Exp/Cntr=0.3,0.1

Type RM Length L Ch R = 1 ,11831   ,182.4,186.3,185.2
XS GIS Cut Line= 4
 2493566.6944381612175.1046067332493700.37499362612480.660162285
2493788.91666031612694.2018289272493827.11110473612784.479606718
#Sta/Elev= 30
       0 1829.69    30.2 1815.52    42.4 1811.03    48.5 1809.58    75.8 1810.14
    87.1 1808.99   117.7 1808.92   135.1 1811.34   148.7 1812.19   200.3 1812.85
   219.7 1812.28   236.8 1809.04   257.4 1809.96   305.4 1809.41   379.2  1810.3
   383.6 1806.86   392.2 1797.48  396.081794.763   400.9 1793.72  412.011794.764
   439.9 1799.29   447.2 1798.59   500.5 1797.84   517.8 1799.36   539.5 1798.43
   543.8 1799.81   556.8 1807.64   604.5 1840.82   639.3 1861.27   662.7 1873.97
#Mann= 8 ,-1 , 0
       0      .1       0  243.31     .12       0  344.14      .1       0
  355.32     .12       0  396.08    .045       0  412.01     .12       0
  444.53      .1       0  645.45      .1       0
#XS Ineff= 2 , 0
                          439.78         1800.11
Permanent Ineff=
       F       F
Bank Sta=396.08,412.01
XS Rating Curve= 0 ,0
Exp/Cntr(USF)=0,0
Exp/Cntr=0.3,0.1

Type RM Length L Ch R = 1 ,11645   ,135,134.8,134.1
XS GIS Cut Line= 4
2493486.83332694612199.4101622852493590.99999365612610.868495598
2493632.66666028612721.9796067332493688.22221583612836.562940046
#Sta/Elev= 30
       0 1819.48    35.7 1815.74      49 1812.56    61.4 1807.67    71.9 1805.95
   110.9 1805.45   160.4 1806.69   197.1 1805.49     214 1803.48   259.4  1803.8
   300.7 1802.35   328.8 1802.61   350.2 1804.47   379.1 1803.96   394.6  1801.8
   411.1  1800.6   428.7 1797.07   441.6 1796.46   454.4 1793.02   483.3 1788.41
   489.31785.958   492.8 1785.19   503.5 1784.89  508.631785.958   522.7  1794.4
   544.1 1801.27   570.8 1813.06   610.8 1833.26   659.7 1856.32   670.4 1860.57
#Mann= 5 ,-1 , 0
       0      .1       0  322.42     .12       0   489.3    .045       0
  508.63     .12       0  582.04      .1       0
Bank Sta=489.3,508.63
XS Rating Curve= 0 ,0
Exp/Cntr(USF)=0,0
Exp/Cntr=0.3,0.1

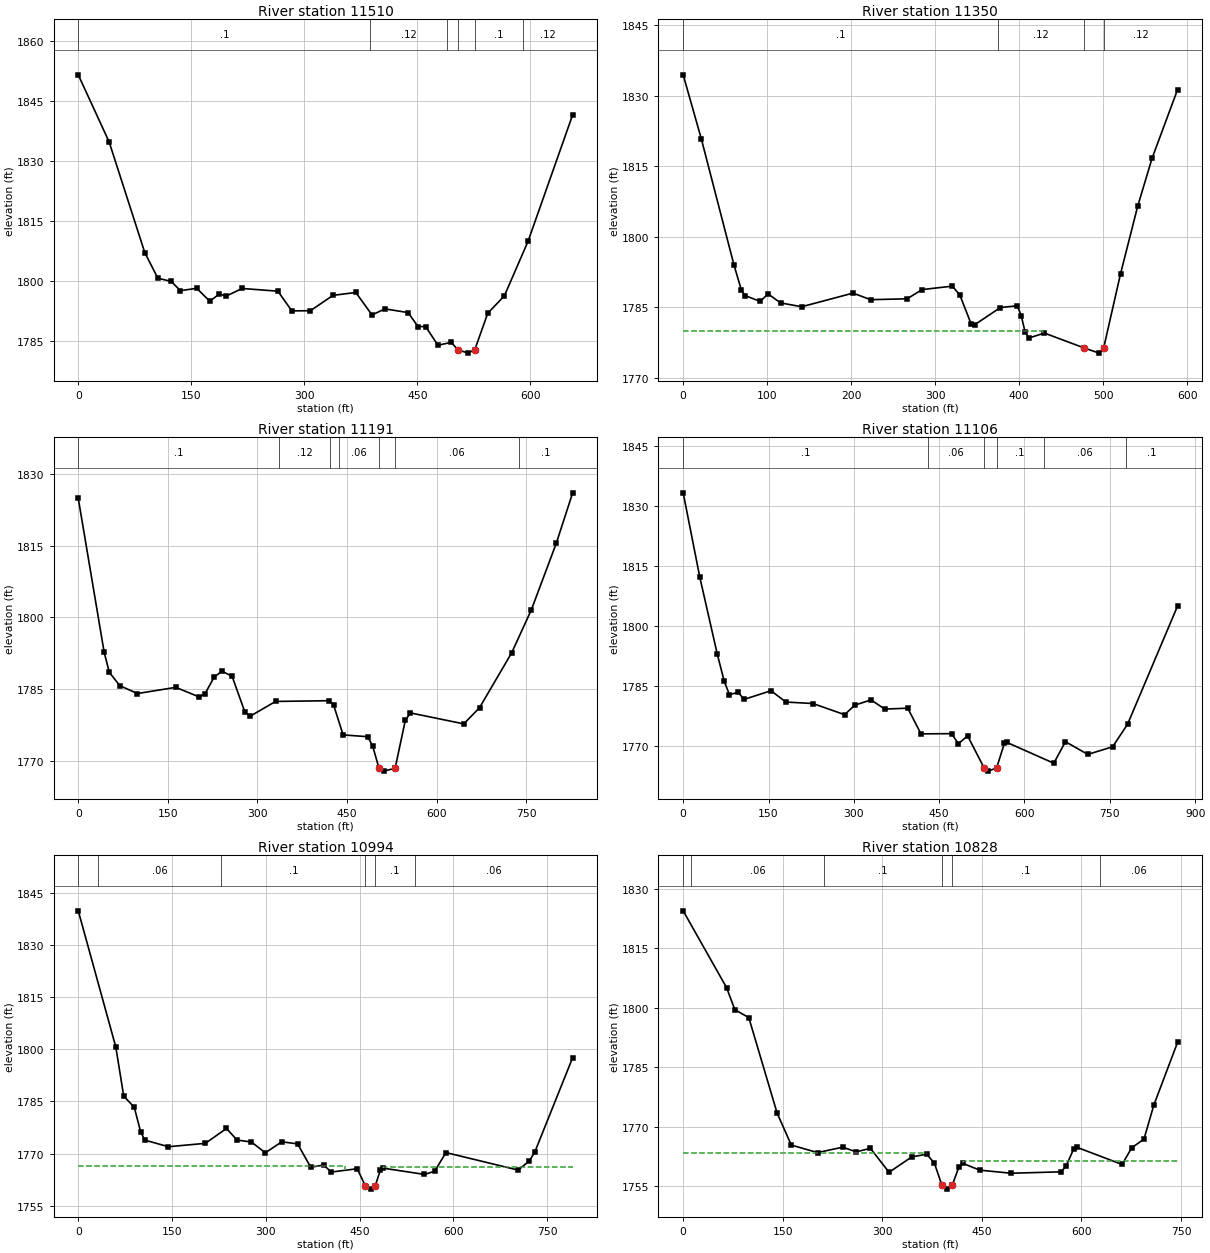
Type RM Length L Ch R = 1 ,11510   ,160.6,159.8,159.2
XS GIS Cut Line= 4
2493304.54166031612268.8546067332493459.05554917612656.007384494
2493523.29166031612794.8962733892493563.22221583 612871.28516227
#Sta/Elev= 30
       0 1851.51      41 1834.74    88.3 1807.09   105.6 1800.72   123.3 1799.91
   135.6  1797.6   157.2 1798.19   174.5 1794.97   187.4 1796.79     196 1796.22
   217.5 1798.15   264.9 1797.47   283.4 1792.55     308 1792.59   338.1 1796.43
   368.3 1797.15   389.8 1791.54     407 1793.05   437.7 1792.13   450.9 1788.63
     461 1788.63   477.3 1783.96   494.9 1784.69   503.71782.877     517    1782
  526.271782.875   543.4 1791.96   565.5 1796.32   596.9 1809.94   656.1 1841.53
#Mann= 6 ,-1 , 0
       0      .1       0  387.71     .12       0  488.77      .1       0
   503.7    .045       0  526.27      .1       0  590.54     .12       0
Bank Sta=503.7,526.27
XS Rating Curve= 0 ,0
Exp/Cntr(USF)=0,0
Exp/Cntr=0.3,0.1

Type RM Length L Ch R = 1 ,11350   ,152.5,158.6,167.2
XS GIS Cut Line= 4
2493156.97221586612412.9518289272493320.16666028612735.868495613
2493412.18054917612892.118495613 2493443.4305492612925.104606733
#Sta/Elev= 30
       0 1834.42    21.7 1820.74    60.4 1794.02    69.4 1788.56    73.9 1787.44
    91.8  1786.2     101 1787.82   115.9  1785.9   141.1 1785.08   202.2 1787.98
   223.1 1786.58   266.6 1786.77   284.5 1788.73   320.4 1789.46   329.3  1787.6
   342.8 1781.44   347.3 1781.28   377.6 1784.91   397.8 1785.29   402.5 1783.15
   407.1 1779.68   411.7 1778.43     430 1779.48     4771776.335   495.3 1775.21
  500.631776.333   520.7  1792.1   541.2 1806.53   558.2 1816.65   588.6 1831.28
#Mann= 4 ,-1 , 0
       0      .1       0  374.22     .12       0     477    .045       0
  500.63     .12       0
#XS Ineff= 2 , 0
          428.81 1779.94
Permanent Ineff=
       F       F
Bank Sta=477,500.63
XS Rating Curve= 0 ,0
Exp/Cntr(USF)=0,0
Exp/Cntr=0.5,0.3

Type RM Length L Ch R = 1 ,11191   ,84.8,85.4,83.9
XS GIS Cut Line= 4
2493141.34721586612442.4657178372493264.61110473612763.646273375
2493250.72221583613046.6323845092493340.99999362613225.451828942
#Sta/Elev= 30
       0 1824.89    43.3 1792.72    51.9  1788.5    69.5 1785.69      99 1784.03
   163.3 1785.33   201.8 1783.35     212 1783.95   227.4 1787.45   240.4 1788.71
   257.5 1787.66   278.9 1780.18   287.5 1779.27   330.4 1782.38   419.4 1782.53
   427.4 1781.67   443.4 1775.37   484.5    1775   492.9 1773.04  503.481768.389
   511.5 1767.79  530.451768.391   547.5 1778.41     556 1779.98   645.4 1777.68
   671.8 1781.07   725.8 1792.61   758.6 1801.58   800.3  1815.5   827.7 1826.05
#Mann= 7 ,-1 , 0
       0      .1       0  336.46     .12       0  421.45      .1       0
  436.05     .06       0  503.48    .045       0  530.45     .06       0
  737.97      .1       0
#XS Ineff= 2 ,-1
       0     455 1770.48     575827.6644 1770.48
Permanent Ineff=
       F       F
Bank Sta=503.48,530.45
XS Rating Curve= 0 ,0
Exp/Cntr(USF)=0,0
Exp/Cntr=0.5,0.3

Type RM Length L Ch R = 1 ,11106   ,115.8,111.8,106.5
XS GIS Cut Line= 4
2493099.68054917612459.8268289422493215.99999362612744.549051151
2493165.65277141613084.826828927 2493255.9305492613282.743495613
#Sta/Elev= 30
       0 1833.22    29.2 1812.22    59.9 1793.05    72.2 1786.22    81.4 1782.91
    96.7  1783.5     107 1781.73   154.5 1783.89   180.5 1781.07     228  1780.7
   283.9 1777.92   301.5 1780.28   330.2 1781.61   354.4 1779.31   394.8 1779.54
     418 1773.14   471.7 1773.19   483.8 1770.69     500 1772.64  529.061764.644
   536.4 1763.85  550.991764.643   564.7  1770.8   568.7 1771.03   651.5 1765.82
     672 1771.19   711.3 1768.02   754.9 1769.92   781.3 1775.57   869.1 1805.02
#Mann= 6 ,-1 , 0
       0      .1       0  429.51     .06       0  529.06    .045       0
  550.99      .1       0  633.76     .06       0  778.97      .1       0
#XS Ineff= 1 ,-1
  569.27869.0826 1770.77
Permanent Ineff=
       F
Bank Sta=529.06,550.99
XS Rating Curve= 0 ,0
Exp/Cntr(USF)=0,0
Exp/Cntr=0.5,0.3

Type RM Length L Ch R = 1 ,10994   ,167.7,165.8,164
XS GIS Cut Line= 4
 2492941.6944381612577.8823845092493056.27777138612923.368495598
2493108.36110476613123.0212733892493205.58332694613320.937940046
#Sta/Elev= 30
       0  1839.8    60.1 1800.62    72.7 1786.54    89.6 1783.33    99.7 1776.33
   106.4  1773.9   144.3    1772   203.3 1772.97   237.1 1777.25   253.9 1773.92
     277 1773.35   299.1 1770.26   325.6 1773.41   350.8 1772.82   371.8 1766.11
   392.4 1766.73   404.8 1764.72   446.2 1765.67   459.21760.745   468.8 1759.81
     4751760.745   483.4  1765.4   486.9 1765.86   553.7 1764.04   570.2 1764.95
     588 1770.32   703.5 1765.29   721.4 1767.88   730.4 1770.55   790.8 1797.61
#Mann= 6 ,-1 , 0
       0      .1       0   31.07     .06       0  228.87      .1       0
   459.2    .045       0     475      .1       0  538.49     .06       0
#XS Ineff= 2 , 0
          426.89 1766.57  487.24          1766.2
Permanent Ineff=
       F       F
Bank Sta=459.2,475
XS Rating Curve= 0 ,0
Exp/Cntr(USF)=0,0
Exp/Cntr=0.3,0.1

Type RM Length L Ch R = 1 ,10828   ,206.9,205.4,204.9
XS GIS Cut Line= 4
2492768.08332694612723.7157178372492887.87499365613003.229606718
2492992.04166031 613199.410162272493115.30554917613379.965717837
#Sta/Elev= 30
       0 1824.39    65.4 1805.02    77.8 1799.48    98.9 1797.45   141.5 1773.39
   162.9 1765.32   202.5 1763.42   240.3 1764.79   260.6 1763.61     282  1764.5
   310.2 1758.46   344.4 1762.34   367.1 1763.01   378.5 1760.72  389.641755.284
   397.7 1754.21  405.551755.281   415.4 1759.82   421.1 1760.72   446.7    1759
   493.9 1758.22   569.2 1758.57   576.7 1759.97   588.2  1764.3   593.4 1764.74
   661.2 1760.43   675.7 1764.63   694.2 1766.83   709.1 1775.44   744.8 1791.23
#Mann= 6 ,-1 , 0
       0      .1       0   11.05     .06       0  212.42      .1       0
  389.64    .045       0  405.55      .1       0  627.57     .06       0
#XS Ineff= 2 , 0
          366.53 1763.43   421.4         1761.22
Permanent Ineff=
       F       F
Bank Sta=389.64,405.55
XS Rating Curve= 0 ,0
Exp/Cntr(USF)=0,0
Exp/Cntr=0.3,0.1

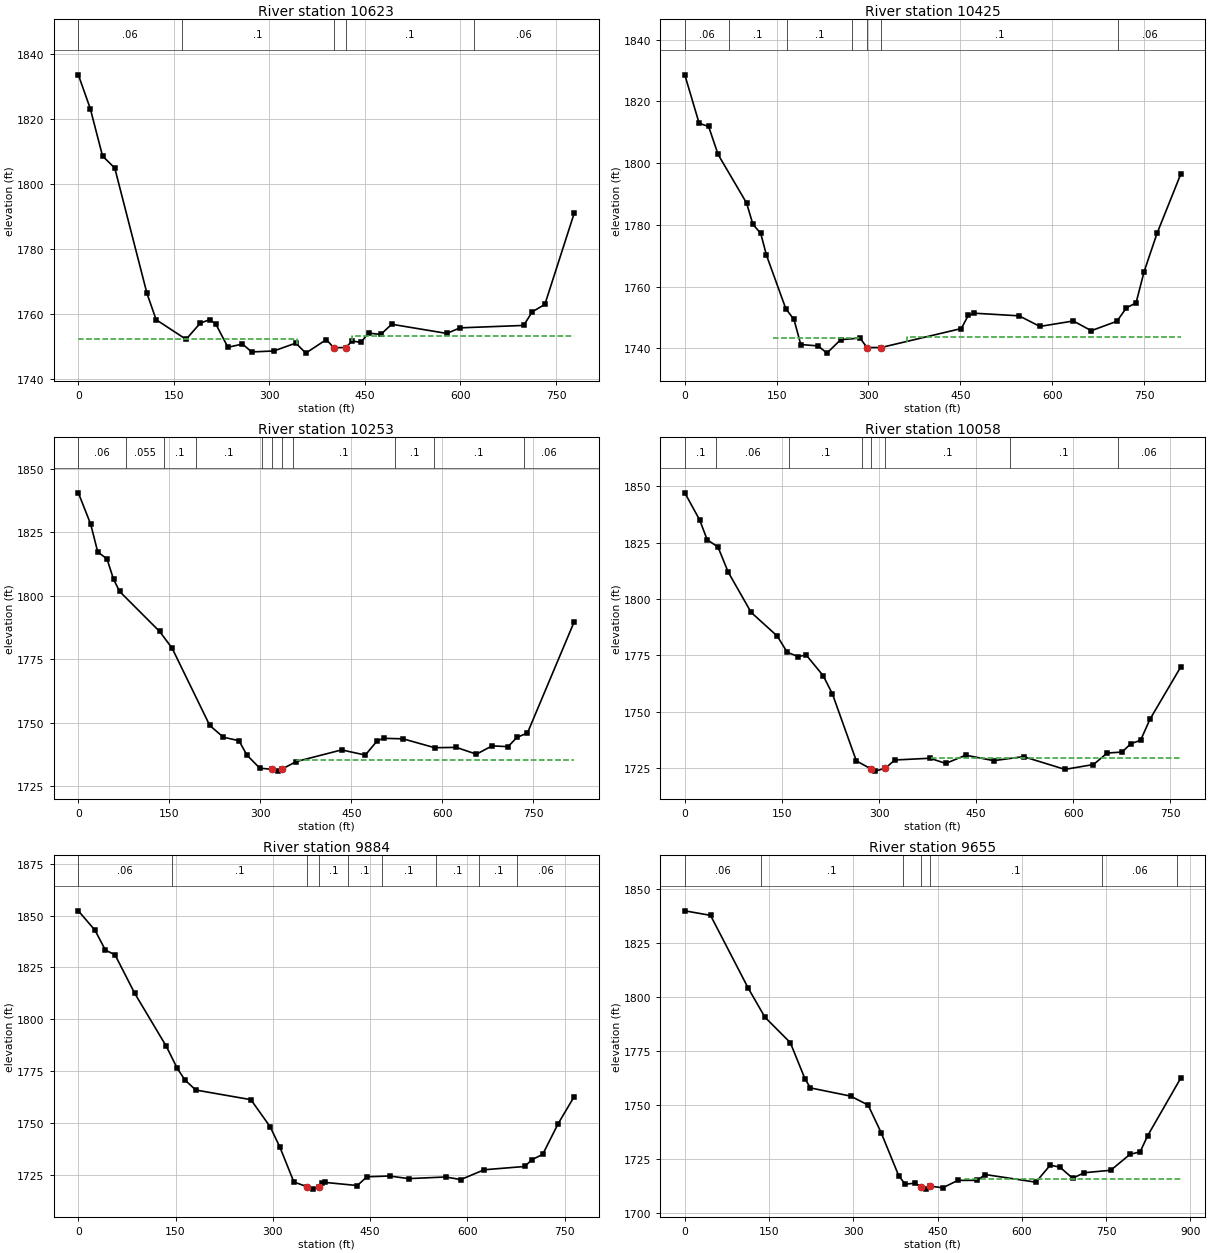
Type RM Length L Ch R = 1 ,10623   ,192.8,197.6,189.9
XS GIS Cut Line= 4
2492577.11110476612911.2157178222492759.40277138613185.521273389
2492867.04166031613315.7296067332493056.27777138613522.326828927
#Sta/Elev= 30
       0 1833.52    18.8 1823.12      38 1808.61    57.2  1804.9   107.7 1766.47
   122.1 1758.36   169.2 1752.32   191.4 1757.29   206.1 1758.36   215.7 1757.06
   234.9 1749.88   257.7 1750.88   272.2 1748.45   306.8 1748.75   341.5 1751.17
   357.1 1748.09   389.5 1752.26   400.9 1749.74   420.8 1749.81   429.3 1751.85
   443.5 1751.36   455.7 1754.25   474.8 1753.82     492 1756.95   578.5 1754.14
   599.4 1755.85   699.2 1756.59   712.7 1760.77   732.5 1763.04   778.5 1790.99
#Mann= 5 ,-1 , 0
       0     .06       0  162.27      .1       0   400.9    .045       0
   420.8      .1       0  621.15     .06       0
#XS Ineff= 2 , 0
           343.7 1752.56  430.07         1753.44
Permanent Ineff=
       F       F
Bank Sta=400.9,420.8
XS Rating Curve= 0 ,0
Exp/Cntr(USF)=0,0
Exp/Cntr=0.3,0.1

Type RM Length L Ch R = 1 ,10425   ,169.5,172.1,168.8
XS GIS Cut Line= 4
2492450.37499365613032.7434955982492589.26388249613202.882384494
2492754.19443807613414.6879400612492938.22221586613678.576828927
#Sta/Elev= 30
       0 1828.64    23.4 1812.95    38.9 1811.91    54.4 1802.83   100.9 1787.11
   111.2 1780.22     124 1777.27   133.4 1770.18     165 1752.86   178.3 1749.38
   189.4 1741.27   217.8 1740.81   232.1 1738.48   254.6 1742.84   286.2 1743.35
   297.6 1740.29   320.4 1740.29   451.6 1746.44   462.9 1750.68   473.1 1751.41
   546.1 1750.56   579.9 1747.13   634.6 1748.89   663.9 1745.75   705.8 1748.81
   721.3 1753.18     737 1754.74   750.1 1764.85   771.2 1777.24   809.8 1796.37
#Mann= 7 ,-1 , 0
       0     .06       0   72.29      .1       0   167.2      .1       0
  272.96      .1       0   297.6    .045       0   320.4      .1       0
  708.05     .06       0
#XS Ineff= 2 ,-1
  143.58  285.47 1743.37  362.09809.7966 1743.76
Permanent Ineff=
       F       F
Bank Sta=297.6,320.4
XS Rating Curve= 0 ,0
Exp/Cntr(USF)=0,0
Exp/Cntr=0.3,0.1

Type RM Length L Ch R = 1 ,10253   ,195.9,195.3,195
XS GIS Cut Line= 4
2492325.37499365613131.7018289272492443.43054917613263.646273375
2492625.72221586613513.6462733892492802.80554917 613793.16016227
#Sta/Elev= 30
       0 1840.46    20.4 1828.09      32 1817.16    47.2 1814.47      58 1806.46
      68 1801.65     134 1785.88   154.6 1779.29   216.6 1748.89     239 1744.26
   264.8 1742.88   277.7 1737.28   299.1 1732.06   319.2 1731.61   329.6  1730.9
   336.3 1731.78   359.2 1734.66   433.9 1739.25   473.1 1737.23   492.7 1742.85
   503.3 1743.82   535.3 1743.61   587.4 1740.12   622.9 1740.25   656.2 1737.57
   682.1 1740.85   708.4 1740.53   722.9 1744.18   740.3 1745.91   817.3 1789.66
#Mann= 11 ,-1 , 0
       0     .06       0   78.22    .055       0  141.15      .1       0
  193.52      .1       0  303.25      .1       0   319.2    .045       0
   336.3      .1       0  353.87      .1       0  521.61      .1       0
  586.57      .1       0  734.37     .06       0
#XS Ineff= 2 , 0
                          360.88         1735.18
Permanent Ineff=
       F       F
Bank Sta=319.2,336.3
XS Rating Curve= 0 ,0
Exp/Cntr(USF)=0,0
Exp/Cntr=0.3,0.1

Type RM Length L Ch R = 1 ,10058   ,175.2,174.1,168.7
XS GIS Cut Line= 4
2492195.16666031613274.0629400462492306.27777138613416.424051166
2492507.66666031 613652.535162272492667.38888249613876.493495613
#Sta/Elev= 30
       0 1847.13    23.1 1835.02    34.5 1826.37    51.3 1823.09      67    1812
   102.5 1794.11   142.8 1783.62   158.3 1776.42   174.8 1774.55   187.5 1775.22
   213.9    1766   228.1 1757.92     265 1728.27  287.041724.792   294.2 1723.72
     310 1725.06   324.5 1728.66   378.6 1729.43   403.2 1727.14     434 1730.79
   477.2 1728.36   523.3 1730.15   587.2  1724.5   631.4 1726.64   652.5 1731.75
   675.5 1732.17   689.1 1735.88   704.2  1737.4   718.5 1746.66     766 1769.82
#Mann= 8 ,-1 , 0
       0      .1       0   48.59     .06       0  160.26      .1       0
   274.3      .1       0  287.04    .045       0     310      .1       0
  502.82      .1       0  668.85     .06       0
#XS Ineff= 2 , 0
                           379.7         1729.56
Permanent Ineff=
       F       F
Bank Sta=287.04,310
XS Rating Curve= 0 ,0
Exp/Cntr(USF)=0,0
Exp/Cntr=0.3,0.1

Type RM Length L Ch R = 1 ,9884    ,228.1,228.6,228.5
XS GIS Cut Line= 4
2492026.76388252613432.0490511512492200.37499362613572.674051166
2492446.90277138613754.9657178372492622.24999365613911.215717837
#Sta/Elev= 30
       0 1852.32    25.7 1842.95    41.8 1833.35    56.6 1831.11    87.1 1812.45
   135.7 1786.99   152.7 1776.29   164.7 1770.64   181.2 1765.89   266.2 1761.24
     296 1748.13   310.9 1738.36   332.5 1721.54  352.361719.313   361.7 1718.09
  370.911719.314   375.6 1721.14   380.6 1721.33   430.3 1719.82   445.3 1724.05
   480.1 1724.41   509.7 1723.16   566.7 1723.95     590  1722.7   626.1 1727.43
   688.5 1729.01   699.8  1732.3   716.3 1734.82   740.3 1749.71   764.9 1762.69
#Mann= 9 ,-1 , 0
       0     .06       0  144.67      .1       0  352.36    .045       0
  370.91      .1       0  415.71      .1       0  467.81      .1       0
   551.1      .1       0  618.62      .1       0  677.45     .06       0
Bank Sta=352.36,370.91
XS Rating Curve= 0 ,0
Exp/Cntr(USF)=0,0
Exp/Cntr=0.3,0.1

Type RM Length L Ch R = 1 ,9655    ,152.3,151.5,151.5
XS GIS Cut Line= 4
2491868.77777138613555.3129400462492089.26388249613765.382384509
 2492254.1944381613895.5907178222492563.22221583614095.243495613
#Sta/Elev= 30
       0 1839.94    45.8 1837.84   113.2 1803.94   142.6 1790.64   187.8 1778.83
   213.9 1762.05   223.7 1757.83   295.1 1754.04   326.3 1749.89   349.4 1737.15
   380.7 1717.19   392.1  1713.2   409.2 1713.64  420.351712.024   428.7 1710.91
   436.1 1712.31   459.3 1711.54   486.1 1714.97   520.4 1714.98   534.8 1717.68
   624.9 1714.13   650.5 1722.03   667.9 1721.07   690.3 1715.97   711.3 1718.52
   758.2 1719.65   792.3 1727.01   810.6 1728.23   824.1 1735.77   882.6 1762.29
#Mann= 7 ,-1 , 0
       0     .06       0  135.22      .1       0  387.58      .1       0
  420.35    .045       0   436.1      .1       0  742.72     .06       0
  876.51      .1       0
#XS Ineff= 1 ,-1
  499.38 882.584 1715.48
Permanent Ineff=
       F
Bank Sta=420.35,436.1
XS Rating Curve= 0 ,0
Exp/Cntr(USF)=0,0
Exp/Cntr=0.3,0.1