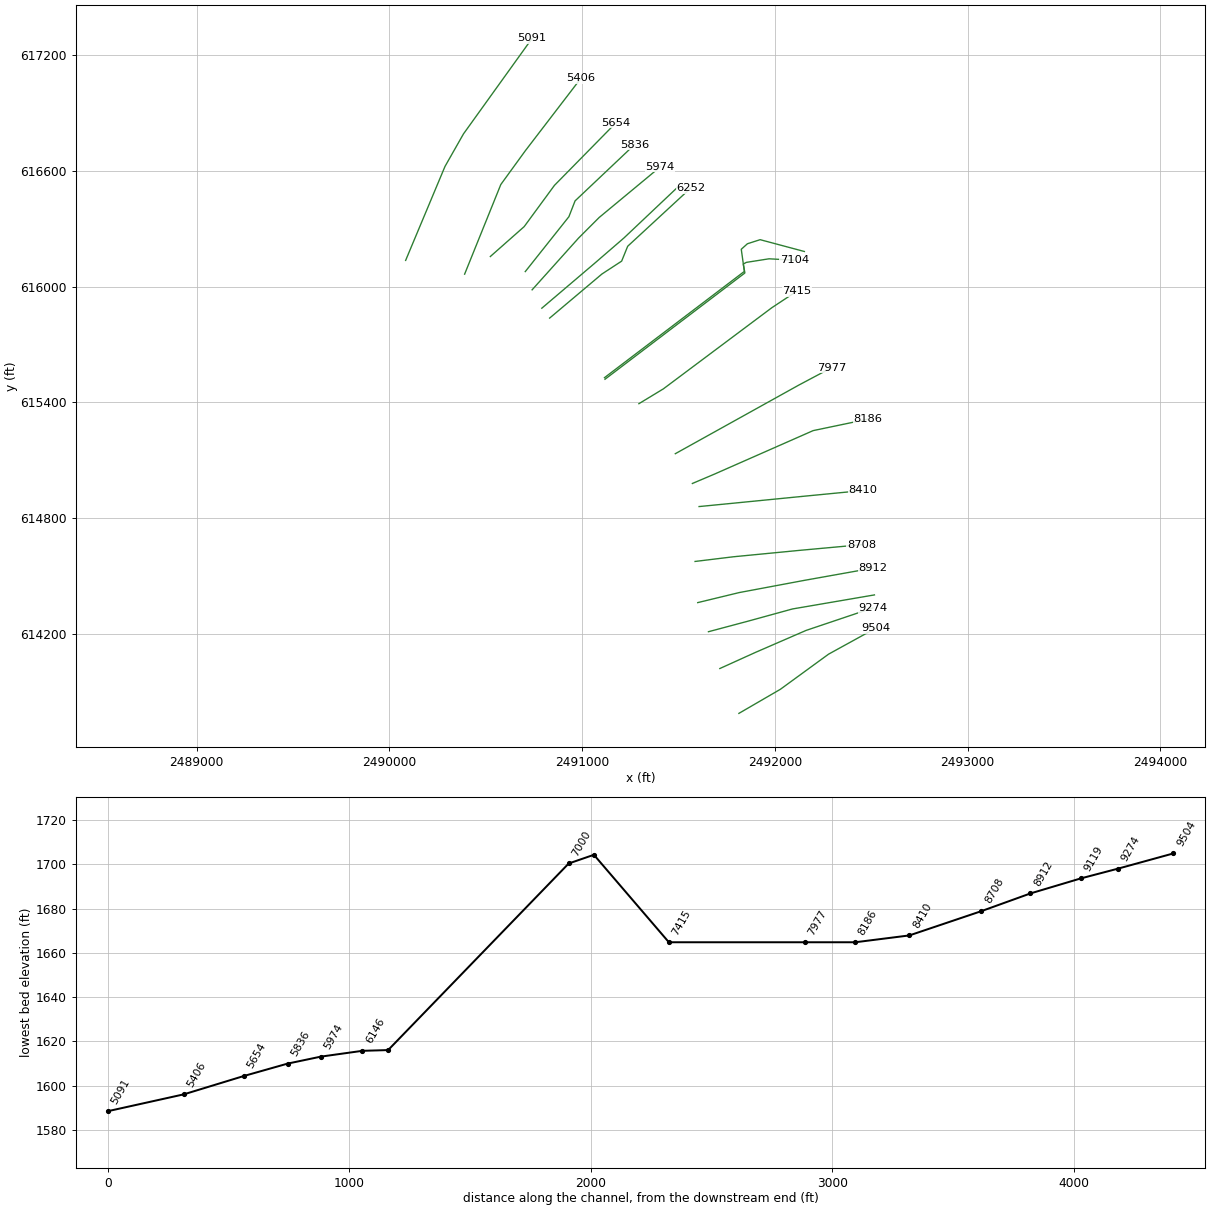
HEC-RAS study DICERN.prj: DICERN

--- DICERN.g01 (geometry) --- (continued)

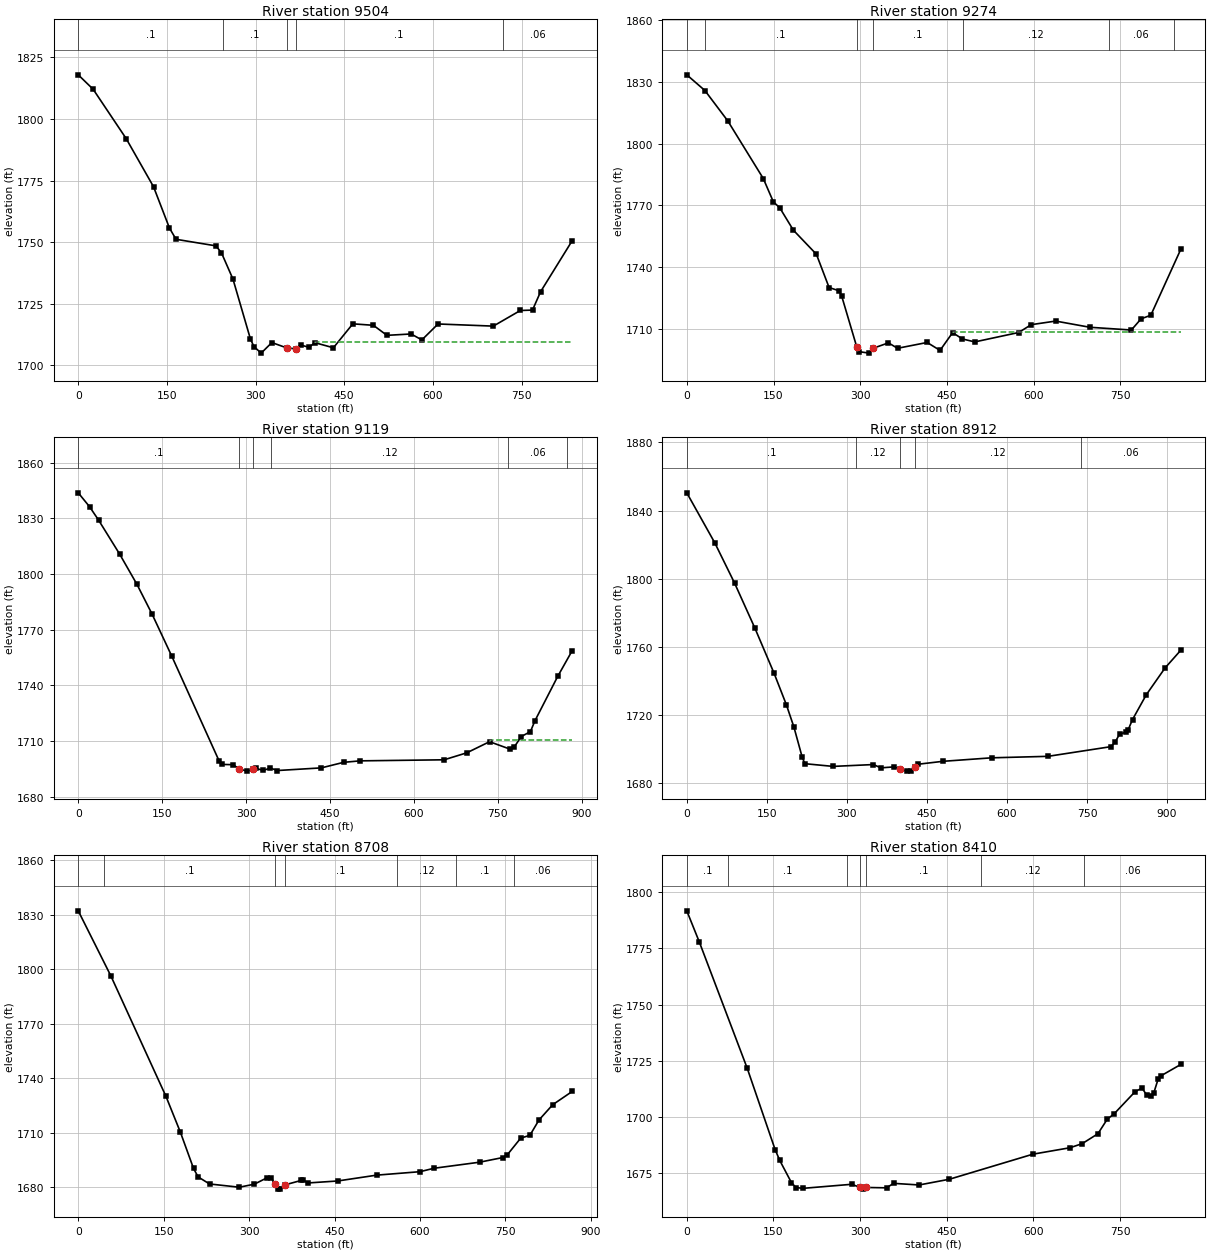
Type RM Length L Ch R = 1 ,9504    ,233.4,229.3,225.9
XS GIS Cut Line= 4
2491813.22221583613786.2157178222492028.49999362613911.215717837
2492278.49999365614093.507384509 2492521.5555492614227.187940061
#Sta/Elev= 30
       0 1817.94    25.2 1812.09      81  1792.1   127.4 1772.52   154.4 1755.72
   165.5 1751.19     233 1748.53   242.3 1745.72   261.8 1735.04   291.3 1710.77
   297.2 1707.68   309.5    1705   327.6 1709.29   353.4 1707.07   367.7 1706.78
   376.3  1708.3   390.6 1707.36   400.2 1709.26   431.7 1707.17   464.6 1716.89
   499.4 1716.29   522.3 1712.22   563.2 1712.77   581.4 1710.36   608.8 1716.83
   702.3 1715.96     748  1722.3   768.6 1722.47   782.3 1729.93   835.7 1750.61
#Mann= 5 ,-1 , 0
       0      .1       0  245.44      .1       0   353.4    .045       0
   367.7      .1       0  718.34     .06       0
#XS Ineff= 2 , 0
                          401.08         1709.64
Permanent Ineff=
       F       F
Bank Sta=353.4,367.7
XS Rating Curve= 0 ,0
Exp/Cntr(USF)=0,0
Exp/Cntr=0.3,0.1

Type RM Length L Ch R = 1 ,9274    ,156.3,155,152.9
XS GIS Cut Line= 4
2491714.26388252614018.8546067332491898.29166031614102.187940046
 2492162.1805492614216.7712733892492507.66666031614333.090717822
#Sta/Elev= 30
       0 1833.39    31.3 1825.77    70.8 1811.03   132.3 1782.99   149.8  1771.6
   160.6 1768.84   184.3 1757.89   224.2 1746.16   246.1 1730.01   263.6  1728.4
   267.9 1725.85   294.1    1701   298.4 1698.82   315.4 1698.12  321.881700.448
   348.8 1703.11   364.5 1700.47   415.7  1703.3     438 1699.45   459.8  1708.1
   476.5 1705.02   498.1 1703.57   573.9 1708.14   595.8 1711.96     638  1713.7
   697.1 1710.69   768.9 1709.35   785.7 1714.78   802.6 1716.55   854.3 1748.53
#Mann= 7 ,-1 , 0
       0      .1       0   32.12      .1       0   294.1    .045       0
  321.88      .1       0  478.01     .12       0  729.62     .06       0
  841.91      .1       0
#XS Ineff= 1 ,-1
  460.91854.2505 1708.34
Permanent Ineff=
       F
Bank Sta=294.1,321.88
XS Rating Curve= 0 ,0
Exp/Cntr(USF)=0,0
Exp/Cntr=0.3,0.1

Type RM Length L Ch R = 1 ,9119    ,205.7,207.6,204.4
XS GIS Cut Line= 4
2491655.23610476614209.826828927 2491863.5694381614265.382384494
2492090.99999365614327.8823844942492516.34721583614400.799051166
#Sta/Elev= 30
       0 1843.71    20.2 1836.24    36.4 1828.98      74 1810.69   105.1 1794.29
     132 1778.33   167.2 1755.67   252.1    1699   256.2 1697.31     277 1697.14
   287.8  1694.8   301.9 1693.68   311.9 1694.74   318.5 1695.11   330.9 1694.06
   343.4 1695.37   355.8    1694   434.6 1695.43   474.6 1698.43     504 1699.22
   654.1 1699.79   694.7 1703.56   735.3 1709.54   772.6 1705.47   779.9 1706.91
   792.1 1712.32   808.4 1715.01   816.5 1720.85   857.1 1744.71     883  1758.6
#Mann= 6 ,-1 , 0
       0      .1       0   287.8    .045       0   311.9      .1       0
  344.78     .12       0  768.89     .06       0  873.88     .12       0
#XS Ineff= 2 , 0
                          736.63         1710.22
Permanent Ineff=
       F       F
Bank Sta=287.8,311.9
XS Rating Curve= 0 ,0
Exp/Cntr(USF)=0,0
Exp/Cntr=0.3,0.1

Type RM Length L Ch R = 1 ,8912    ,201.2,203.3,201.6
XS GIS Cut Line= 4
 2491599.6805492614360.8684956132491814.95832694614412.951828942
2492148.29166028614475.4518289422492507.66666031614539.687940061
#Sta/Elev= 30
       0 1850.43    52.5 1821.02    89.6 1797.37   127.7 1770.89   163.7 1744.33
   186.5 1726.01   200.7 1712.88   216.3 1695.09   221.3 1691.29   274.2  1689.7
   349.8 1690.78   363.7 1688.84   387.5 1689.39   400.3 1688.15   412.5 1686.92
   420.7 1687.21   427.4 1689.12   432.9 1690.95     480 1692.68   571.2 1694.74
   676.9 1695.61   794.7 1701.29   802.9 1704.01     811 1708.63   823.2 1709.78
   827.2 1711.21   835.4 1717.25   861.2 1731.81   896.3 1747.52   925.7 1757.91
#Mann= 5 ,-1 , 0
       0      .1       0   316.9     .12       0   400.3    .045       0
   427.4     .12       0  738.66     .06       0
Bank Sta=400.3,427.4
XS Rating Curve= 0 ,0
Exp/Cntr(USF)=0,0
Exp/Cntr=0.3,0.1

Type RM Length L Ch R = 1 ,8708    ,295.9,298.3,294.5
XS GIS Cut Line= 4
2491585.79166031 614574.410162272491785.44443807614598.715717822
2492125.72221583614631.7018289422492448.63888249614661.215717837
#Sta/Elev= 30
       0  1832.2    57.4 1796.28   154.1 1729.96   179.5 1710.16   202.4 1690.34
   210.5 1685.63   230.6 1681.75   282.8 1679.96   309.2 1681.63     331 1685.08
   339.1 1684.99   345.4 1681.74   351.1 1678.91   355.1 1679.01   362.6 1681.22
   391.3 1683.69   395.3  1683.8   403.4 1682.31   455.3 1683.39   523.9 1686.61
   600.3 1688.52   624.4 1690.39   704.7 1693.74   745.6 1696.31     753 1697.67
     777 1707.01   793.1 1708.55   809.1 1717.02   833.2 1725.42   867.3  1732.7
#Mann= 7 ,-1 , 0
       0      .1       0   45.66      .1       0   345.4    .045       0
   362.6      .1       0  560.17     .12       0  662.73      .1       0
  765.28     .06       0
Bank Sta=345.4,362.6
XS Rating Curve= 0 ,0
Exp/Cntr(USF)=0,0
Exp/Cntr=0.3,0.1

Type RM Length L Ch R = 1 ,8410    ,241.7,223.9,427.8
XS GIS Cut Line= 4
2491606.62499365614859.1323845092491766.34721583614874.757384494
2492170.86110473614914.6879400462492457.31943807614942.465717837
#Sta/Elev= 30
       0 1791.76    21.9 1777.75   104.6 1721.69   152.8 1685.56   160.9 1680.69
     181 1670.87     189 1668.64   201.1 1668.28   285.4 1670.08     300 1668.69
   305.6 1667.93   309.6 1668.67   345.8 1668.51   357.8  1670.5   402.1 1669.78
   454.3 1672.32     599 1683.48   663.3 1686.35   684.3 1688.17   711.5 1692.57
   727.6 1699.02   739.7 1701.48   775.8 1711.28   787.9 1712.92   795.9 1709.76
     804 1709.55     808 1710.59     816 1717.13     820 1718.26   854.8 1723.39
#Mann= 7 ,-1 , 0
       0      .1       0   71.22      .1       0  276.69      .1       0
     300    .045       0   309.6      .1       0  508.88     .12       0
  687.62     .06       0
Bank Sta=300,309.6
XS Rating Curve= 0 ,0
Exp/Cntr(USF)=0,0
Exp/Cntr=0.3,0.1

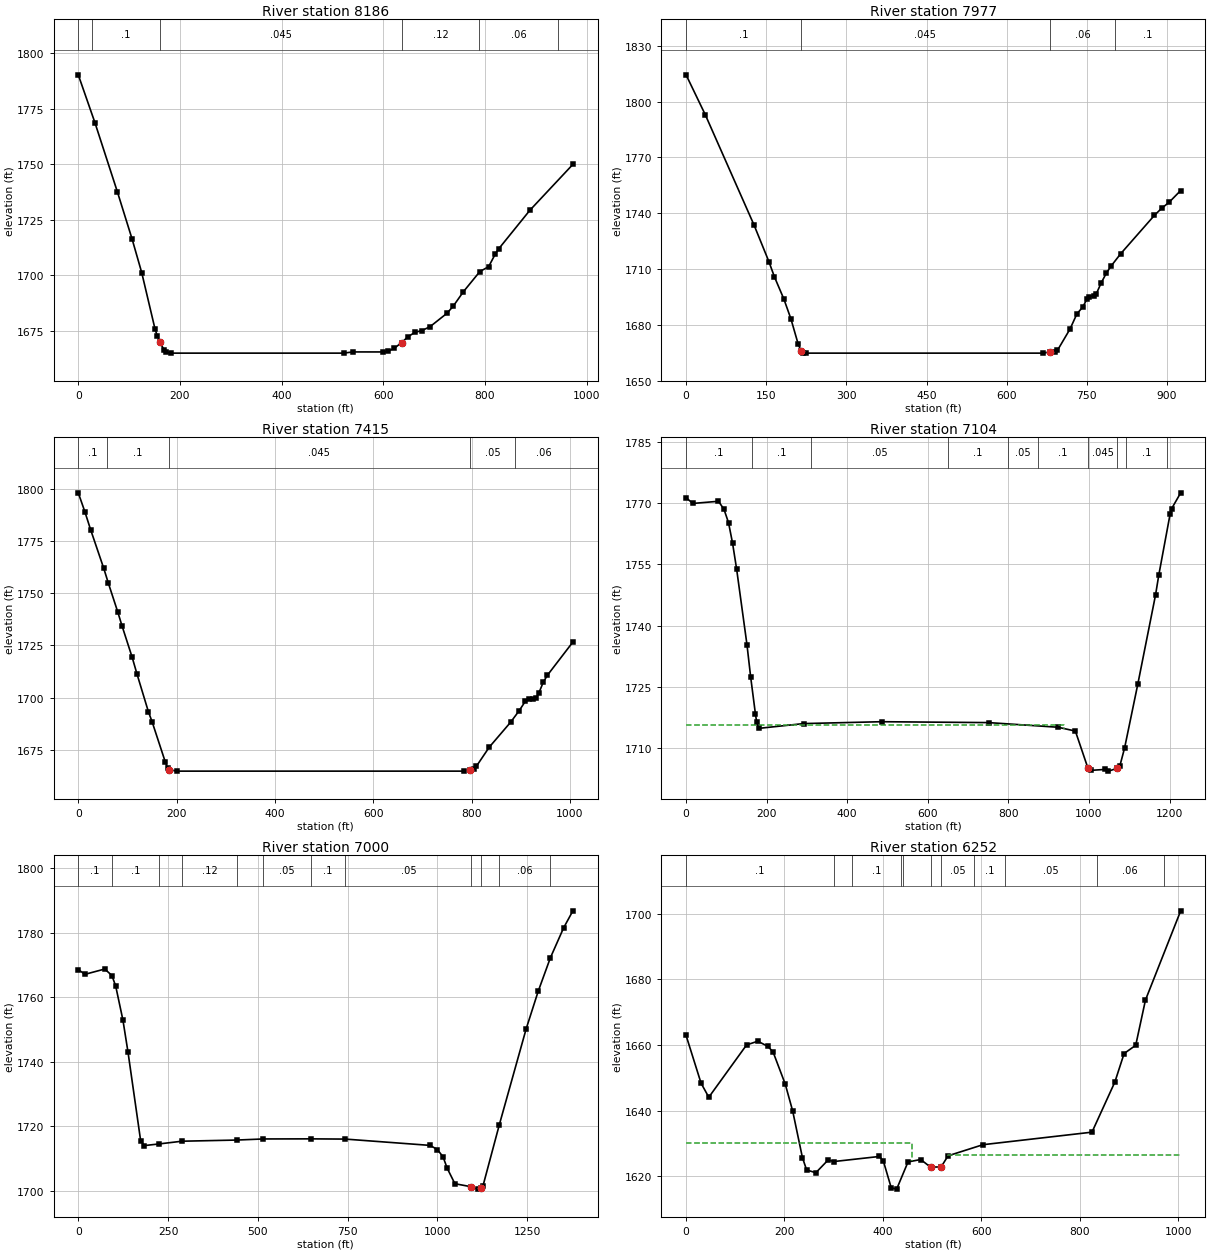
Type RM Length L Ch R = 1 ,8186    ,201.8,209.1,242.3
XS GIS Cut Line= 4
2491571.90277138614978.9240511662491686.48610473615027.535162285
2492198.63888252615253.2296067332492481.62499365615312.257384494
#Sta/Elev= 30
       0 1790.22    32.7 1768.72      77 1737.47   105.9 1716.24   124.8 1701.14
     151 1675.72   155.3 1672.69   160.6 1669.84   168.5 1666.38   172.8 1665.24
   181.6 1664.84   522.5 1664.84     540 1665.38     599 1665.37   609.6  1665.7
   621.8    1667   636.2 1669.62   649.1 1672.25   662.4 1674.23   676.4 1675.01
   692.5 1676.82   725.1 1682.73   737.4 1685.88   757.8 1692.52   790.2  1701.6
   807.4 1703.78   820.9 1709.65   827.6 1711.93   888.5 1729.18   973.2 1749.87
#Mann= 6 ,-1 , 0
       0      .1       0   26.39      .1       0   160.6    .045       0
   636.2     .12       0  788.79     .06       0  944.16      .1       0
Bank Sta=160.6,636.2
XS Rating Curve= 0 ,0
Exp/Cntr(USF)=0,0
Exp/Cntr=0.3,0.1

Type RM Length L Ch R = 1 ,7977    ,343.6,562.8,418.1
XS GIS Cut Line= 4
2491483.36110476615133.4379400462491639.61110473615220.243495613
2492123.98610473615489.3407178372492294.12499362615579.618495598
#Sta/Elev= 30
       0 1814.34    35.9 1792.94   127.1 1733.71   154.9 1714.06   165.3 1705.84
     183 1693.89   196.1 1683.32   209.8 1669.68   215.4 1665.79   218.9 1664.94
   223.5 1664.84   667.4 1664.84   680.1  1665.4   690.2 1665.58   694.9 1666.33
   718.4 1677.78   731.4 1685.96     742 1689.51   750.8 1694.18   754.1  1695.1
   763.1 1695.73   767.7 1696.76   776.7 1702.53   786.3 1707.76   794.8 1711.44
   812.9 1718.12   876.3 1738.83   889.9 1742.67   903.5 1745.77   925.5  1752.2
#Mann= 4 ,-1 , 0
       0      .1       0   215.4    .045       0   680.1     .06       0
  803.48      .1       0
Bank Sta=215.4,680.1
XS Rating Curve= 0 ,0
Exp/Cntr(USF)=0,0
Exp/Cntr=0.5,0.3

Type RM Length L Ch R = 1 ,7415    ,856.5,310.5,281.6
XS GIS Cut Line= 4
2491294.47221586615392.8129400612491421.55554917615469.896273375
2491984.05554917615890.7296067182492113.22221586615976.146273389
#Sta/Elev= 30
       0 1797.96    13.4 1788.92      25 1780.41    51.8 1761.86    61.1 1754.82
    80.3 1740.99    88.8 1734.46   109.5 1719.37   119.7 1711.08   142.8 1693.13
   150.2 1688.43     177  1669.2   181.6 1666.43   184.5 1665.54   200.1 1664.84
   784.6 1664.84     796 1665.57   804.7 1665.95   809.5 1667.08     836 1676.33
   879.2 1688.19   896.5 1693.66   909.4 1698.28   916.7 1699.19   925.4 1699.13
   931.2 1699.73   936.9 1702.27   945.7 1707.35   954.2 1710.72    1006 1726.59
#Mann= 5 ,-1 , 0
       0      .1       0   58.45      .1       0   184.5    .045       0
     796     .05       0  888.28     .06       0
Bank Sta=184.5,796
XS Rating Curve= 0 ,0
Exp/Cntr(USF)=0,0
Exp/Cntr=0.5,0.3

Type RM Length L Ch R = 1 ,7104    ,119.6,104.3,108.3
XS GIS Cut Line= 6
 2491118.5154406615519.6222608162491844.28037744616070.982952733
2491835.90457673616117.1831211282491851.73820668616125.933675966
2491969.69011819616144.5194883082492101.12792461616137.065023772
#Sta/Elev= 30
       0 1771.32    16.8 1769.91    80.3 1770.44    93.9 1768.53   105.4 1765.19
   115.3 1760.24   125.4  1753.9   151.1 1735.37   160.3 1727.44     172 1718.47
   175.3 1716.35   180.3 1714.84     292 1716.01   485.3 1716.47   751.2 1716.25
   923.6 1715.11   966.3 1714.18   997.5 1705.09  1003.9 1704.55  1040.3 1704.79
  1048.4 1704.37  1070.3 1705.06  1076.8 1705.68  1088.5 1710.05  1121.1 1725.59
  1165.3 1747.51  1173.3 1752.35  1201.3 1767.24  1205.3 1768.65  1227.7 1772.51
#Mann= 10 ,-1 , 0
       0      .1       0  164.69      .1       0  311.02     .05       0
  651.13      .1       0  797.93     .05       0  874.45      .1       0
   997.5    .045       0  1070.3     .06       0 1091.06      .1       0
 1194.36     .12       0
#XS Ineff= 2 , 0
          939.09 1715.65
Permanent Ineff=
       F       F
Bank Sta=997.5,1070.3
XS Rating Curve= 0 ,0
Exp/Cntr(USF)=0,0
Exp/Cntr=0.5,0.3

Type RM Length L Ch R = 1 ,7000    ,351.9,747.7,401
XS GIS Cut Line= 6
2491115.79556562615527.7818857472491841.56050246616079.142577664
2491825.44608191616193.9305503912491857.26861914616222.489237649
2491923.36158108 616243.704262472492152.80554917616182.396273389
#Sta/Elev= 30
       0 1768.51    18.7 1767.06    73.7  1768.7    93.7 1766.69   104.3 1763.37
   124.3  1752.9   138.5 1742.93   173.7 1715.46   183.7 1713.94   223.7 1714.44
   288.8  1715.3   441.5 1715.66   515.7    1716   647.2 1716.03   743.8 1715.96
   980.2    1714  1000.3 1712.69  1015.9 1710.46  1027.5  1706.9  1048.9 1702.12
  1094.6 1701.17  1114.5 1700.44    1122 1700.77  1126.9 1701.35  1172.6  1720.4
  1247.5 1750.19  1280.8 1761.77  1314.8 1772.18  1351.7 1781.47  1377.5 1786.75
#Mann= 12 ,-1 , 0
       0      .1       0    93.7      .1       0   223.7      .1       0
   288.8     .12       0   441.5      .1       0   515.7     .05       0
   647.2      .1       0   743.8     .05       0  1094.6    .045       0
    1122      .1       0  1172.6     .06       0  1314.8      .1       0
Bank Sta=1094.6,1122
XS Rating Curve= 0 ,0
Exp/Cntr(USF)=0,0
Exp/Cntr=0.3,0.1

Type RM Length L Ch R = 1 ,6252    ,104.3,106.3,95.6
XS GIS Cut Line= 5
2490831.38805136615836.9463836772491102.80554917616065.729606718
2491204.88888252616132.3962733892491236.13888249616209.479606718
2491563.22221586616511.562940046
#Sta/Elev= 30
       0 1662.91    30.5 1648.35    46.2 1644.09     123 1660.02   145.8 1661.15
   166.6 1659.55   176.9 1657.84   201.6 1648.07   216.7 1639.88   236.5 1625.69
     245 1621.95   263.7 1621.09   288.5 1624.94   300.9 1624.51   393.1 1626.05
     401 1624.64     417  1616.5     428  1616.1   451.1 1624.38   476.9 1625.12
 496.8581622.799 518.4391622.867   532.5 1626.25   603.4 1629.63     825 1633.45
   871.5 1648.71   890.3  1657.4   913.9 1659.91   933.7 1673.68  1005.3 1700.86
#Mann= 11 ,-1 , 0
       0      .1       0   300.9      .1       0  338.11      .1       0
 436.122      .1       0  441.69     .12       0 496.858    .045       0
 518.439     .05       0  585.41      .1       0  648.94     .05       0
  834.49     .06       0  971.09      .1       0
#XS Ineff= 2 , 0
          458.71 1630.14  533.33         1626.35
Permanent Ineff=
       F       F
Bank Sta=496.858,518.439
XS Rating Curve= 0 ,0
Exp/Cntr(USF)=0,0
Exp/Cntr=0.3,0.1

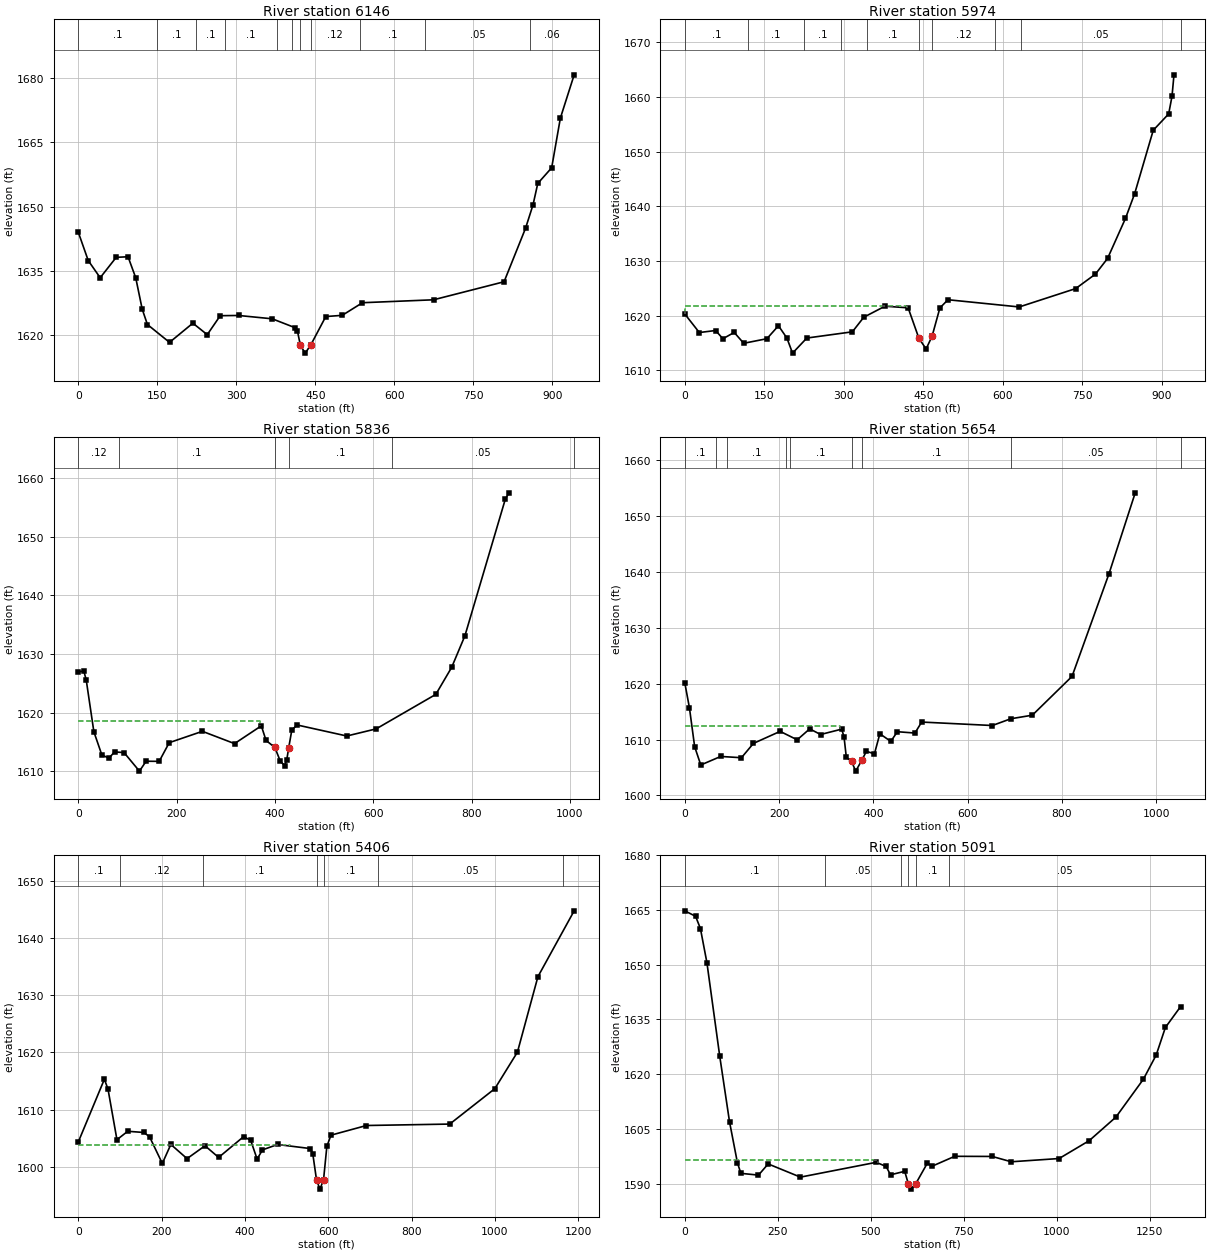
Type RM Length L Ch R = 1 ,6146    ,168.4,171.8,171.9
XS GIS Cut Line= 4
2490790.82557466615888.2859002122491063.22221583616119.896273389
2491215.99999365616251.8407178372491493.77777141616514.340717822
#Sta/Elev= 30
       0 1643.97    18.8 1637.38    41.5 1633.37    71.9 1638.13    94.4 1638.27
     109 1633.36   121.3 1626.04   131.2 1622.45   173.2 1618.28   217.5 1622.76
   244.8 1620.08   269.5 1624.51   304.4 1624.56   368.3 1623.78   411.1 1621.73
   416.1 1620.93 421.7281617.557   430.9 1615.77  441.691617.738   469.9 1624.31
   501.1 1624.59   539.6 1627.54   674.5 1628.22   808.5 1632.43   849.3 1644.93
   863.5  1650.4   872.5 1655.38   898.9 1659.04   915.4 1670.63   941.6 1680.74
#Mann= 11 ,-1 , 0
       0      .1       0  149.21      .1       0  223.66      .1       0
  278.05      .1       0  377.02      .1       0  406.57     .12       0
 421.728    .045       0  441.69     .12       0  534.57      .1       0
  658.88     .05       0  856.95     .06       0
#XS Ineff= 2 , 0
          308.64 1624.32
Permanent Ineff=
       F       F
Bank Sta=421.728,441.69
XS Rating Curve= 0 ,0
Exp/Cntr(USF)=0,0
Exp/Cntr=0.3,0.1

Type RM Length L Ch R = 1 ,5974    ,130.2,138,141.8
XS GIS Cut Line= 4
2490740.47063908615983.6062209372490981.27777141616251.840717837
2491088.22221583616358.7851622852491404.88888249 616621.28516227
#Sta/Elev= 30
       0 1620.31    27.4 1616.92    58.2 1617.29    71.9 1615.78    93.2 1616.94
   111.2 1614.95   154.9 1615.79   176.7 1618.16   192.6 1615.92   203.3 1613.15
   230.2 1615.91   316.2 1617.05   337.7 1619.72   377.8 1621.74   421.4 1621.44
   441.7 1615.87   455.3 1613.91   466.6 1616.25   481.3 1621.42   496.6 1622.92
     631  1621.6   737.5 1624.96   774.8 1627.61   797.7 1630.48   831.5 1637.81
   848.8 1642.33   883.9 1653.94     913 1656.93   919.3 1660.17     923 1664.08
#Mann= 10 ,-1 , 0
       0      .1       0  118.93      .1       0  225.73      .1       0
  294.24      .1       0  344.64      .1       0   441.7    .045       0
   466.6     .12       0  584.71      .1       0  633.59     .05       0
  935.54     .06       0
#XS Ineff= 2 , 0
          418.88 1621.76
Permanent Ineff=
       F       F
Bank Sta=441.7,466.6
XS Rating Curve= 0 ,0
Exp/Cntr(USF)=0,0
Exp/Cntr=0.3,0.1

Type RM Length L Ch R = 1 ,5836    ,180.9,182.4,178.3
XS GIS Cut Line= 4
2490704.92306588616078.1183140362490931.27777141616362.951828942
2490963.22221583616444.8962733752491271.55554917616736.562940061
#Sta/Elev= 30
       0 1626.95    11.2 1627.08    16.1 1625.54    31.6 1616.72    47.9 1612.74
    62.3 1612.21    73.7 1613.27      93 1613.16   124.3 1609.99   137.9 1611.68
   164.5 1611.66   184.9 1614.85   252.4 1616.79   317.8 1614.69   372.3 1617.73
   381.9 1615.23   399.8 1614.04     411 1611.67   419.6 1610.95   423.9 1611.84
     428 1613.98   434.4 1617.04   445.3 1617.87   546.2 1615.99     606 1617.21
   727.3  1623.1   759.5 1627.71   786.5 1633.11   868.8 1656.48   876.2 1657.53
#Mann= 6 ,-1 , 0
       0     .12       0   82.27      .1       0   399.8    .045       0
     428      .1       0  638.62     .05       0 1008.75     .06       0
#XS Ineff= 2 , 0
          370.27 1618.47
Permanent Ineff=
       F       F
Bank Sta=399.8,428
XS Rating Curve= 0 ,0
Exp/Cntr(USF)=0,0
Exp/Cntr=0.3,0.1

Type RM Length L Ch R = 1 ,5654    ,246.7,247.3,244.8
XS GIS Cut Line= 4
 2490523.7485344616156.4225606942490699.33332694616311.562940061
2490856.27777141616525.4518289422491175.72221586616850.451828942
#Sta/Elev= 30
       0 1620.16     9.8 1615.71    20.9 1608.73    33.9 1605.45    76.2 1606.98
   120.1 1606.75   145.6 1609.32   202.2 1611.47   238.4 1609.96   264.9 1611.92
     288 1610.91   332.7 1611.87   337.7  1610.5   342.6 1606.82   353.6  1606.1
   362.5 1604.35   375.3 1606.28   385.1  1607.9   402.2 1607.45   413.7 1611.04
   436.9 1609.68   450.9 1611.41   488.1 1611.17   502.4 1613.14   652.3 1612.52
   691.4 1613.73   737.1 1614.37   821.3 1621.32   899.8 1639.73   955.3  1654.2
#Mann= 9 ,-1 , 0
       0      .1       0   67.15     .12       0   90.11      .1       0
  214.42     .12       0  223.01      .1       0   353.6    .045       0
   375.3      .1       0   691.4     .05       0 1051.62     .06       0
#XS Ineff= 2 , 0
          330.13 1612.44
Permanent Ineff=
       F       F
Bank Sta=353.6,375.3
XS Rating Curve= 0 ,0
Exp/Cntr(USF)=0,0
Exp/Cntr=0.3,0.1

Type RM Length L Ch R = 1 ,5406    ,313.9,315.6,315.1
XS GIS Cut Line= 4
2490390.27855594616064.9031945222490578.01388255616529.896273389
2490705.09721586616704.8962733752490992.59721586617079.896273389
#Sta/Elev= 30
       0 1604.36    62.5  1615.3    71.2 1613.59    92.7 1604.74   118.6 1606.21
   157.4    1606   170.9 1605.26   201.6 1600.59   222.1 1603.91     261 1601.43
   304.1 1603.68   336.8 1601.64   396.6 1605.26   413.7 1604.64   429.2 1601.35
   442.1 1602.96   478.2  1603.9   557.1 1603.19   562.8 1602.29 571.8981597.671
     580  1596.1  588.611597.696   596.6 1603.56   606.5 1605.53   691.7 1607.22
   891.6 1607.47   999.9 1613.66  1054.1 1620.04  1103.3 1633.23  1190.3 1644.74
#Mann= 7 ,-1 , 0
       0      .1       0  100.04     .12       0  300.37      .1       0
 571.898    .045       0  588.61      .1       0  719.89     .05       0
 1164.46     .06       0
#XS Ineff= 2 , 0
             507 1603.84
Permanent Ineff=
       F       F
Bank Sta=571.898,588.61
XS Rating Curve= 0 ,0
Exp/Cntr(USF)=0,0
Exp/Cntr=0.3,0.1

Type RM Length L Ch R = 1 ,5091    ,197.4,197.8,201.1
XS GIS Cut Line= 4
2490084.26388252616136.146273375 2490288.4305492616623.646273375
2490384.26388255616792.3962733752490740.51388255617288.229606718
#Sta/Elev= 30
       0 1664.77      29 1663.27      42 1659.91    59.4  1650.6      94 1624.86
   120.3 1606.89   141.5 1595.69   150.7 1592.79   198.1  1592.3   224.1 1595.37
   310.9 1591.75   514.7 1595.81   541.3 1594.67   553.1 1592.38   591.3 1593.35
  600.89 1589.93   608.9 1588.46  620.931589.929   651.9 1595.54   665.7 1594.78
   725.7 1597.46   826.5 1597.42   877.7 1595.96  1006.4 1596.85  1087.3 1601.75
  1159.1 1608.21    1233  1618.6  1267.5 1625.25  1292.1 1632.78  1333.1 1638.52
#Mann= 6 ,-1 , 0
       0      .1       0  377.62     .05       0  580.47      .1       0
  600.89    .045       0  620.93      .1       0  710.58     .05       0
#XS Ineff= 2 , 0
          520.44 1596.42
Permanent Ineff=
       F       F
Bank Sta=600.89,620.93
XS Rating Curve= 0 ,0
Exp/Cntr(USF)=0,0
Exp/Cntr=0.3,0.1