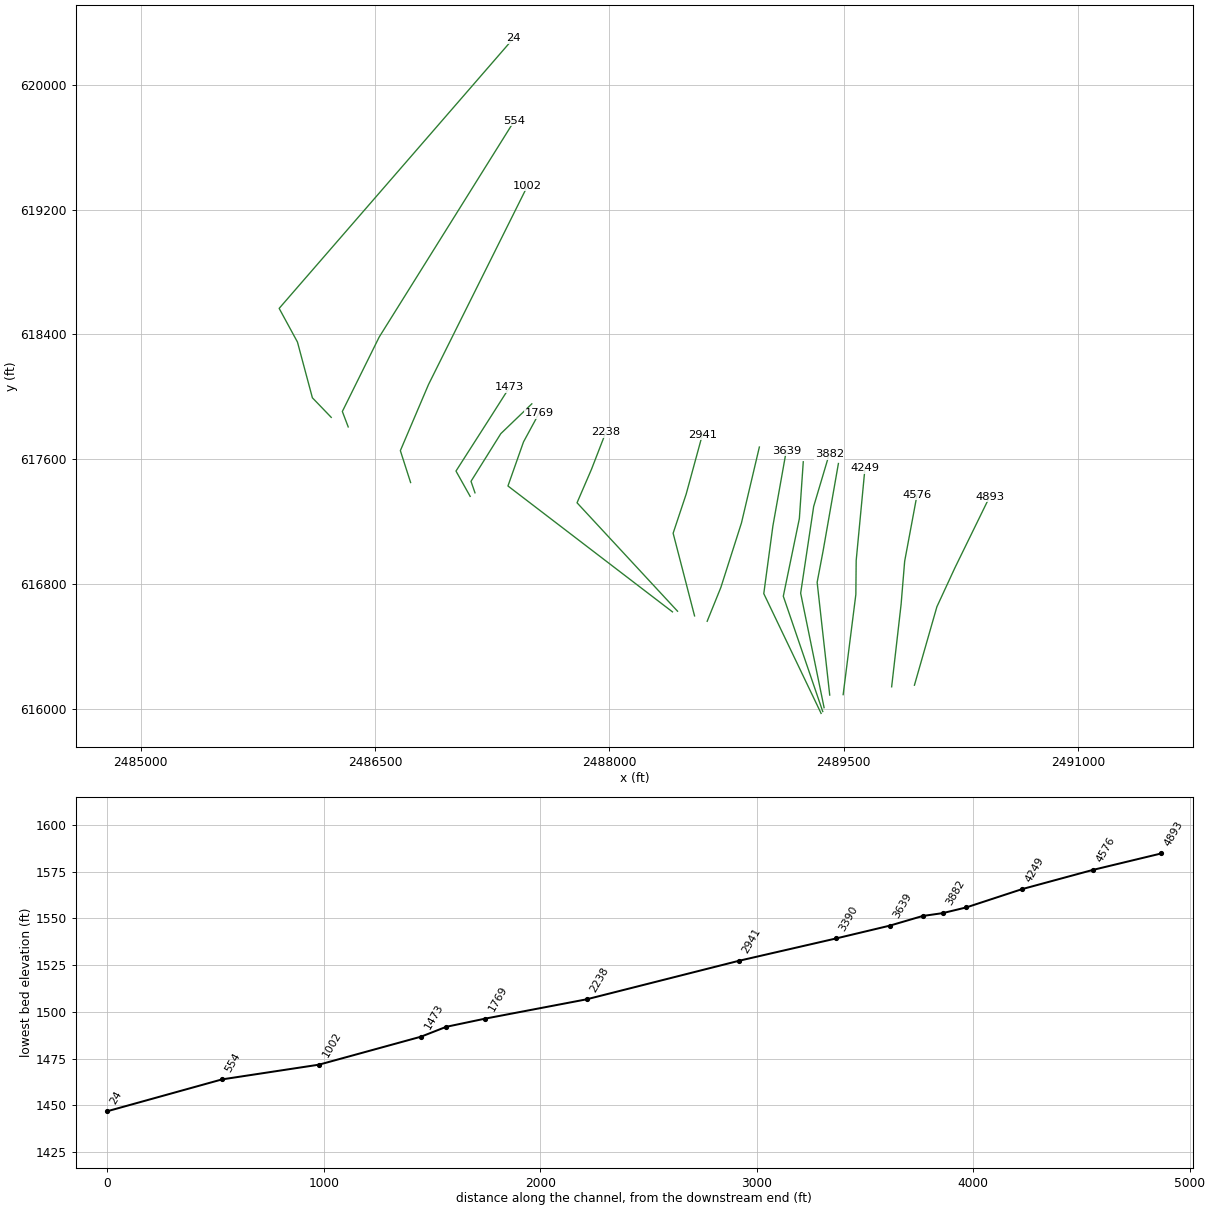
HEC-RAS study DICERN.prj: DICERN

--- DICERN.g01 (geometry) --- (continued)

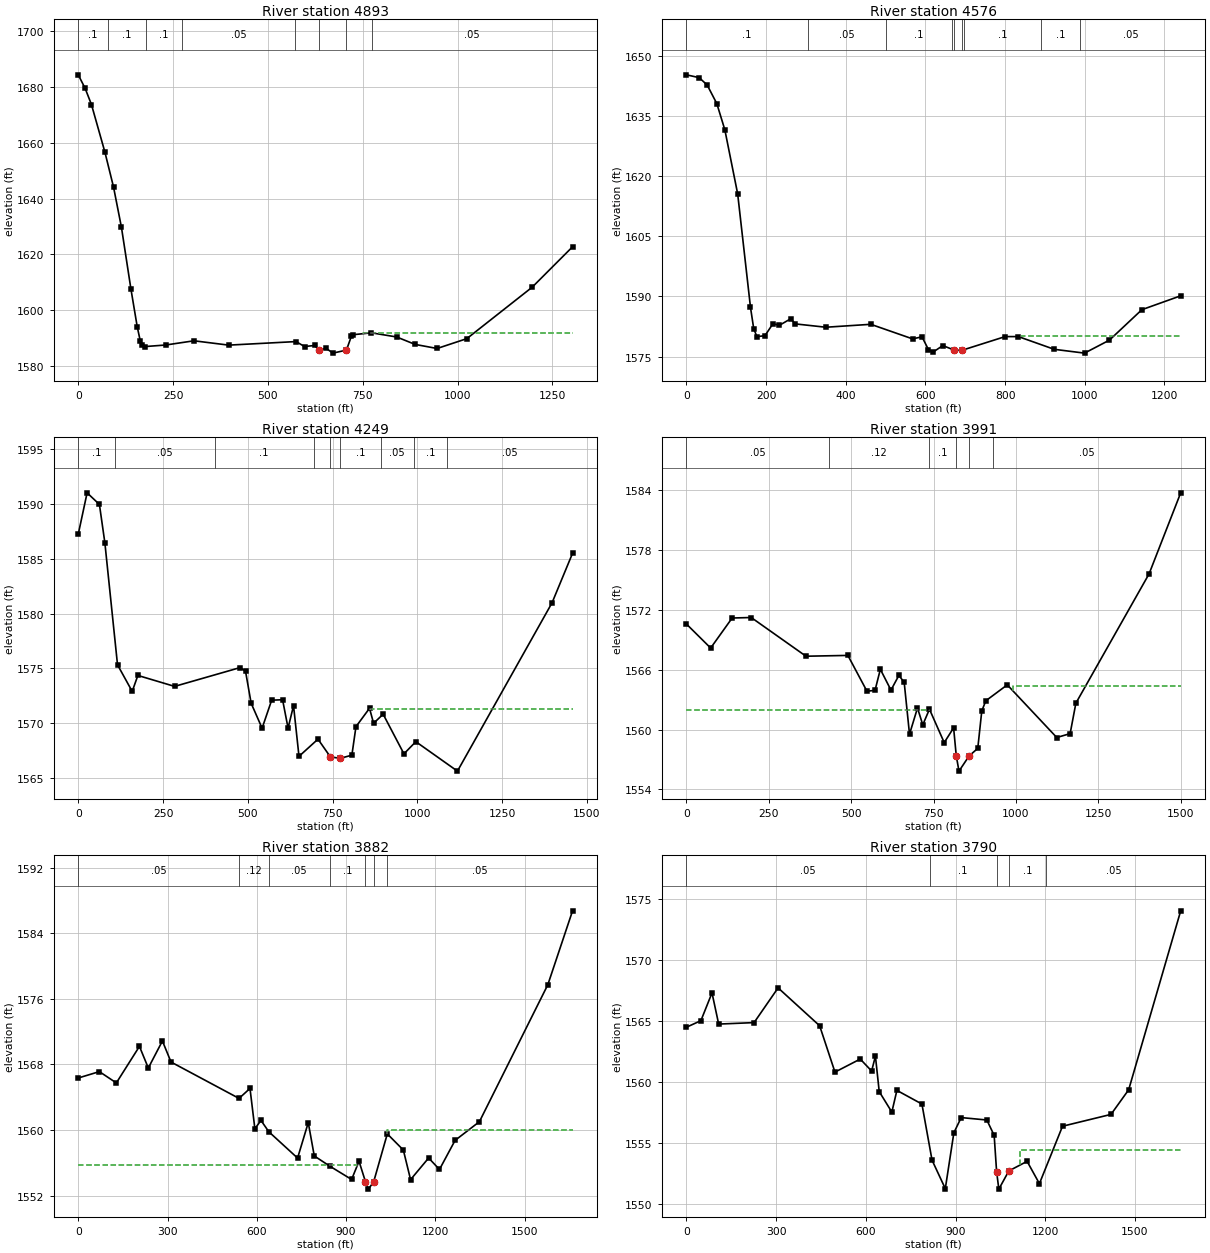
Type RM Length L Ch R = 1 ,4893    ,305.4,317.4,327.7
XS GIS Cut Line= 4
2489953.43054917616153.4379400612490097.18054917616655.521273375
2490211.76388252616903.4379400612490434.68054917617359.687940046
#Sta/Elev= 30
       0 1684.23    18.2 1679.37    34.8 1673.61    70.2 1656.62      93 1644.11
   113.9 1629.69   138.8  1607.7   155.5 1594.14   163.8 1588.91   167.9 1587.74
   176.3 1587.08   230.4 1587.63   305.2 1589.14   396.6 1587.59   574.2 1588.86
   596.5 1587.09   622.9 1587.46  635.671585.818   653.8 1586.42   671.4 1584.73
  707.121585.817   719.9 1590.71   724.3 1591.31   773.1 1591.99   839.3 1590.51
   888.3 1587.84   946.1 1586.39  1024.5 1589.91  1196.8 1608.31  1303.2 1622.75
#Mann= 8 ,-1 , 0
       0      .1       0   77.55      .1       0  177.29      .1       0
  274.15     .05       0  570.54      .1       0  635.67    .045       0
  707.12      .1       0  773.45     .05       0
#XS Ineff= 2 ,-1
       0  564.61 1588.63  750.891303.167 1591.96
Permanent Ineff=
       F       F
Bank Sta=635.67,707.12
XS Rating Curve= 0 ,0
Exp/Cntr(USF)=0,0
Exp/Cntr=0.3,0.1

Type RM Length L Ch R = 1 ,4576    ,320.7,326.8,326.8
XS GIS Cut Line= 4
2489807.59721583616143.0212733892489868.01388255616670.104606733
 2489890.9305492616947.1879400462489970.09721586617372.187940046
#Sta/Elev= 30
       0 1645.21    32.1 1644.51    52.2 1642.66    76.4 1638.03    96.5 1631.51
   128.7 1615.55   160.9 1587.26     169 1581.97     177 1579.98   197.2 1580.23
   217.3 1583.21   233.4 1582.81   261.6 1584.42   273.6 1583.16   350.1 1582.33
   462.9 1583.06   567.8 1579.43   591.5 1579.94   607.6 1576.76   619.6 1576.16
   643.7 1577.76   672.8 1576.62   691.9 1576.59   800.2    1580   833.4    1580
   923.4 1576.83   999.5 1575.88    1062 1579.12  1143.4  1586.7  1240.9 1590.16
#Mann= 9 ,-1 , 0
       0      .1       0  304.92     .05       0  500.15      .1       0
  667.95      .1       0   672.8    .045       0   691.9      .1       0
  695.66      .1       0  891.05      .1       0  988.63     .05       0
#XS Ineff= 1 ,-1
  839.231240.875 1580.18
Permanent Ineff=
       F
Bank Sta=672.8,691.9
XS Rating Curve= 0 ,0
Exp/Cntr(USF)=0,0
Exp/Cntr=0.3,0.1

Type RM Length L Ch R = 1 ,4249    ,261.1,257.3,257.2
XS GIS Cut Line= 4
 2489497.1805492616093.021273389 2489578.4305492616734.687940061
2489580.51388252616951.3546067332489636.76388252617543.021273375
#Sta/Elev= 30
       0 1587.25    26.1 1591.03    62.4 1589.97    78.5 1586.46   115.8 1575.32
   159.1 1572.89   175.8 1574.35   284.1 1573.35   477.7 1575.07   493.4 1574.72
   509.9 1571.81   542.2 1569.53   570.4 1572.09   602.6 1572.13   618.8 1569.54
   634.9 1571.59     651 1566.96     707 1568.53   743.6 1566.91  772.851566.779
     807 1567.07     819 1569.67     859 1571.35     871 1569.98   899.2 1570.81
   960.5 1567.19   995.6  1568.3  1118.3 1565.61  1397.4 1580.99  1457.8 1585.51
#Mann= 9 ,-1 , 0
       0      .1       0  109.16     .05       0  401.87      .1       0
  695.07      .1       0   743.6    .045       0  772.85      .1       0
  891.94     .05       0  989.64      .1       0 1087.35     .05       0
#XS Ineff= 2 , 0
                          860.36         1571.31
Permanent Ineff=
       F       F
Bank Sta=743.6,772.85
XS Rating Curve= 0 ,0
Exp/Cntr(USF)=0,0
Exp/Cntr=0.3,0.1

Type RM Length L Ch R = 1 ,3991    ,107,109.1,104.1
XS GIS Cut Line= 4
2489411.18517879 616090.023588212489330.62962326616812.245810419
2489369.51851213617017.8013659722489466.74073434617573.356921539
#Sta/Elev= 30
       0 1570.58    73.6 1568.17   138.8 1571.18   196.7 1571.23   362.9 1567.35
     490 1567.43   547.9 1563.84   572.4 1563.93   588.5 1566.04   620.7 1563.95
   644.8 1565.43   660.9 1564.72     677 1559.53   701.2 1562.16   717.3 1560.47
   737.5 1562.04   782.3 1558.69   810.8 1560.17  818.881557.358   827.1 1555.83
     8581557.359   884.1 1558.11   896.3 1561.86   908.5 1562.88   973.6 1564.48
  1123.8  1559.2  1164.4 1559.59  1181.8 1562.64    1404 1575.61  1499.9 1583.73
#Mann= 6 ,-1 , 0
       0     .05       0     433     .12       0  735.86      .1       0
  818.88    .045       0     858      .1       0  931.04     .05       0
#XS Ineff= 2 , 0
          735.25 1561.97  992.04         1564.35
Permanent Ineff=
       F       F
Bank Sta=818.88,858
XS Rating Curve= 0 ,0
Exp/Cntr(USF)=0,0
Exp/Cntr=0.5,0.3

Type RM Length L Ch R = 1 ,3882    ,93.2,92.7,92.5
XS GIS Cut Line= 4
2489375.07406771616009.4680326432489225.07406768616742.801365986
2489308.40740103617298.3569215242489408.40740103617634.468032643
#Sta/Elev= 30
       0 1566.34    70.9 1567.12     128 1565.74   205.6  1570.2   235.4 1567.56
   282.8 1570.86   311.7 1568.29   540.3 1563.85   577.1 1565.07   593.5 1560.14
   613.9 1561.17   640.4 1559.78     737 1556.57   772.9  1560.9   793.1 1556.83
     845 1555.59   918.5 1553.96   943.5 1556.18  965.151553.684     975 1552.78
  992.741553.683  1038.5 1559.52  1092.4 1557.55  1116.7 1553.94  1177.4 1556.58
  1213.8 1555.18  1266.3 1558.73    1348 1561.01  1577.9 1577.72    1661 1586.74
#Mann= 7 ,-1 , 0
       0     .05       0   540.3     .12       0   640.4     .05       0
     845      .1       0  965.15    .045       0  992.74      .1       0
  1038.5     .05       0
#XS Ineff= 3 ,-1
       0     935 1555.68    1022    1038 1555.68    1038 1660.96    1560
Permanent Ineff=
       F       F       F
Bank Sta=965.15,992.74
XS Rating Curve= 0 ,0
Exp/Cntr(USF)=0,0
Exp/Cntr=0.5,0.3

Type RM Length L Ch R = 1 ,3790    ,152.1,150.9,156.6
XS GIS Cut Line= 4
2489366.44503255615984.8033752852489113.96295658616723.356921539
2489216.74073437617220.5791437632489241.74073437617584.468032643
#Sta/Elev= 30
       0 1564.52    48.5 1565.06    85.6 1567.34   107.9 1564.78   226.3  1564.9
   306.6 1567.75   445.6 1564.64   496.8 1560.84   581.3 1561.91   619.4 1560.93
   632.1 1562.15   644.8 1559.24     687 1557.56   703.9 1559.34   787.6 1558.22
   821.4 1553.62   865.8 1551.28   894.4 1555.86   918.9 1557.11  1004.7 1556.91
  1029.2 1555.65 1037.371552.666  1044.8 1551.241078.2151552.731  1139.3 1553.52
  1180.5 1551.69  1257.8  1556.4  1419.9 1557.37    1479 1559.39    1653 1574.07
#Mann= 5 ,-1 , 0
       0     .05       0  813.27      .1       0 1037.37    .045       0
1078.215      .1       0 1203.88     .05       0
#XS Ineff= 2 , 0
          945.68 1556.32 1115.21         1554.49
Permanent Ineff=
       F       F
Bank Sta=1037.37,1078.215
XS Rating Curve= 0 ,0
Exp/Cntr(USF)=0,0
Exp/Cntr=0.5,0.3

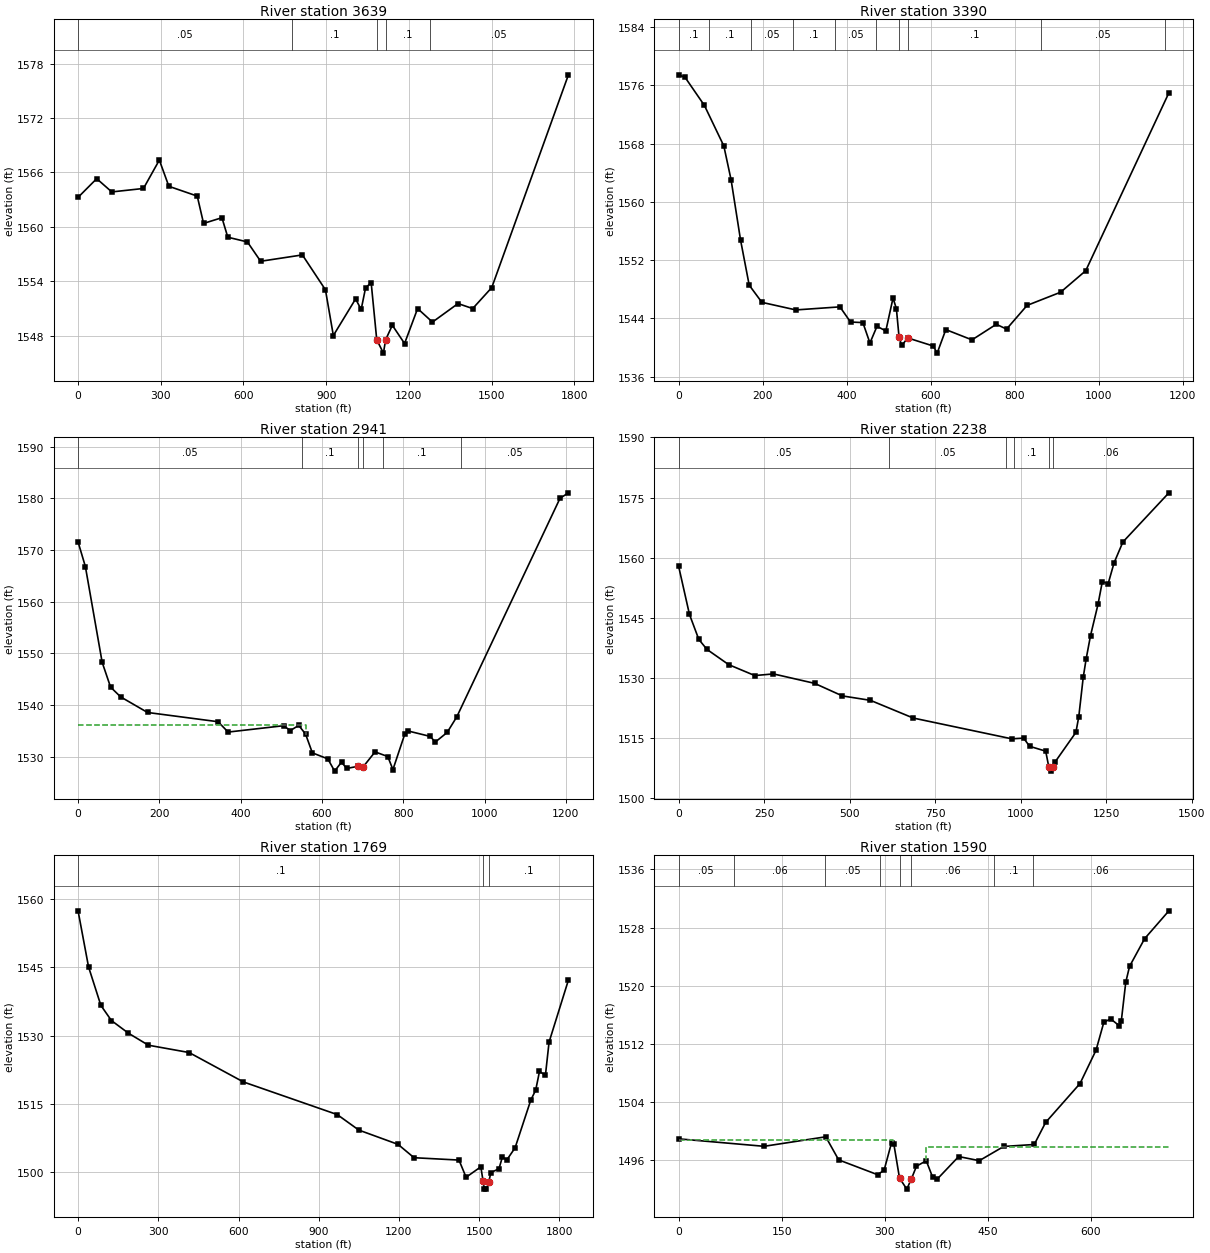
Type RM Length L Ch R = 1 ,3639    ,252.9,248.7,247.1
XS GIS Cut Line= 4
2489355.90365892615972.9292082792488988.96295661616740.023588195
2489047.29628992617173.3569215392489133.40740106617656.690254867
#Sta/Elev= 30
       0 1563.26    67.6 1565.32   122.3 1563.86   237.2 1564.24   294.8 1567.37
   329.3 1564.48   432.3  1563.4   455.2 1560.39   521.8 1561.02   543.1 1558.87
   614.2 1558.35   662.2 1556.22   813.6 1556.92   897.2 1553.08   925.9 1548.04
  1006.6 1552.07  1026.8 1550.91  1042.9 1553.31  1063.1 1553.85 1083.291547.577
  1107.5  1546.11115.5791547.576  1139.8 1549.17  1184.2 1547.16  1231.5 1551.01
  1285.4 1549.52  1378.1 1551.56  1431.3 1551.01  1500.4 1553.32  1778.5 1576.76
#Mann= 5 ,-1 , 0
       0     .05       0  775.07      .1       0 1083.29    .045       0
1115.579      .1       0 1275.97     .05       0
#XS Ineff= 2 , 0
         1056.24 1553.59
Permanent Ineff=
       F       F
Bank Sta=1083.29,1115.579
XS Rating Curve= 0 ,0
Exp/Cntr(USF)=0,0
Exp/Cntr=0.3,0.1

Type RM Length L Ch R = 1 ,3390    ,447.3,449.4,446.5
XS GIS Cut Line= 4
2488626.54428776616562.9357499752488714.19443807616779.606921539
2488846.13888249617192.8013659862488960.72221583617678.912477091
#Sta/Elev= 30
       0 1577.43    15.5 1577.09    61.6 1573.23   107.8 1567.67   125.1 1563.02
   147.6 1554.76   168.2 1548.56   198.4  1546.2   279.2 1545.16   384.1 1545.58
   409.3  1543.5   438.7 1543.42   455.5 1540.62   472.3 1542.91   493.3 1542.28
   510.5  1546.8   518.5 1545.31   524.81541.426   531.1 1540.28   545.51541.313
     606 1540.21   615.5 1539.23   636.1 1542.46   698.4 1541.05   756.2 1543.19
   780.6 1542.53   829.4 1545.78   909.2 1547.59     969 1550.54  1166.9 1574.96
#Mann= 10 ,-1 , 0
       0      .1       0   72.87      .1       0  173.05     .05       0
  272.65      .1       0  371.37     .05       0  470.09      .1       0
   524.8    .045       0   545.5      .1       0  863.18     .05       0
 1156.66     .06       0
#XS Ineff= 2 , 0
          511.93 1546.33
Permanent Ineff=
       F       F
Bank Sta=524.8,545.5
XS Rating Curve= 0 ,0
Exp/Cntr(USF)=0,0
Exp/Cntr=0.3,0.1

Type RM Length L Ch R = 1 ,2941    ,701.4,703.1,701.6
XS GIS Cut Line= 4
2488545.72249253616597.4526862552488408.63888249617126.829143748
2488491.97221586617376.8291437632488596.13888249617758.773588195
#Sta/Elev= 30
       0 1571.57      18 1566.81    59.3 1548.29      80  1543.5   104.8 1541.61
   170.9  1538.6   344.4 1536.81   369.2 1534.81   505.6 1536.04   522.2  1535.1
   542.8  1536.1   559.6 1534.43   576.4 1530.79   614.4 1529.63   631.2 1527.26
   648.1    1529   660.7 1527.78 687.6921528.172 701.7191528.124   730.6 1530.98
   761.9 1530.08   774.6 1527.56   804.1 1534.51   812.5 1535.01   866.4 1533.97
   878.8 1532.88   907.9 1534.73   931.6 1537.74  1185.6    1580  1206.3 1581.06
#Mann= 6 ,-1 , 0
       0     .05       0 551.714      .1       0 687.692    .045       0
 701.719      .1       0 750.937      .1       0 941.027     .05       0
#XS Ineff= 2 , 0
          560.77 1536.27
Permanent Ineff=
       F       F
Bank Sta=687.692,701.719
XS Rating Curve= 0 ,0
Exp/Cntr(USF)=0,0
Exp/Cntr=0.3,0.1

Type RM Length L Ch R = 1 ,2238    ,467.7,468.8,468.7
XS GIS Cut Line= 4
2488436.82646115616627.3869534712487793.40649361617321.832152522
2487885.67648461617535.7180560432487977.28675211617772.377913767
#Sta/Elev= 30
       0 1557.93      32  1545.8    59.3 1539.56    83.2 1537.06   146.6 1533.26
   222.9 1530.53   277.4 1530.94   397.5 1528.59   479.2 1525.44     561 1524.34
   686.1 1519.92     974 1514.73  1008.8  1514.9  1026.3 1512.86  1073.3 1511.65
1082.4361507.705  1088.5 1506.66 1095.971507.715  1100.3 1508.89  1161.6 1516.34
    1170 1520.25    1183 1530.08  1191.6 1534.71  1204.3 1540.49  1226.2  1548.3
  1238.8 1553.97    1256  1553.5  1273.1 1558.67  1298.9 1563.88  1433.4 1576.17
#Mann= 6 ,-1 , 0
       0     .05       0 615.148     .05       0 956.567    .045       0
 982.003      .1       01082.436    .045       0 1095.97     .06       0
Bank Sta=1082.436,1095.97
XS Rating Curve= 0 ,0
Exp/Cntr(USF)=0,0
Exp/Cntr=0.3,0.1

Type RM Length L Ch R = 1 ,1769    ,180.6,179.4,177
XS GIS Cut Line= 4
2488404.39983699616623.0384188972487351.11671179617429.479401007
2487450.52771395617711.3044020962487549.77217042617894.524937108
#Sta/Elev= 30
       0 1557.44    39.2 1545.13    85.3 1536.67   124.8 1533.34   188.5 1530.56
   262.9 1527.93   415.2 1526.32   618.3 1519.86   969.3 1512.69  1049.9 1509.29
  1196.6 1506.15  1256.5 1503.22  1424.6  1502.7  1451.1 1498.92  1506.2 1501.22
1514.682 1498.07  1518.9 1496.43  1527.4 1496.32 1535.891497.887  1543.7 1499.94
  1574.1 1500.81  1586.8 1503.36  1603.3 1502.73  1634.3 1505.39    1693 1515.87
  1711.4 1518.06  1725.6 1522.17  1747.8 1521.32  1761.4 1528.61  1833.8 1542.24
#Mann= 3 , 0 , 0
       0      .1       01514.682    .045       0 1535.89      .1       0
#XS Ineff= 2 , 0
          539.09 1502.95
Permanent Ineff=
       F       F
Bank Sta=1514.682,1535.89
XS Rating Curve= 0 ,0
Exp/Cntr(USF)=0,0
Exp/Cntr=0.5,0.3

Type RM Length L Ch R = 1 ,1590    ,116,116,115.5
XS GIS Cut Line= 4
2487139.98318457 617385.667201742487114.62339977617459.376166455
2487305.47812374617764.7437248082487503.96703667617955.598448779
#Sta/Elev= 30
       0 1498.88   124.5 1497.85   214.2 1499.16     233 1495.98   289.6 1493.94
   299.1 1494.56   309.9 1498.34   313.2  1498.2 321.518 1493.47   332.1 1491.95
 338.9341493.391   346.2 1495.11   360.4 1495.86   369.8 1493.57   376.7 1493.36
   407.6 1496.44   437.6 1495.87   473.1 1497.83   517.5  1498.1   534.1 1501.14
   584.1  1506.5   607.4 1511.09   618.7 1514.92   628.5 1515.42   641.3 1514.46
   644.2 1515.14   650.7 1520.48   656.2 1522.65   678.1 1526.46   713.4  1530.3
#Mann= 8 ,-1 , 0
       0     .05       0   80.44     .06       0  213.83     .05       0
  292.64     .06       0 321.518    .045       0 338.934     .06       0
  458.76      .1       0  515.22     .06       0
#XS Ineff= 2 , 0
          312.66 1498.67   360.3          1497.7
Permanent Ineff=
       F       F
Bank Sta=321.518,338.934
XS Rating Curve= 0 ,0
Exp/Cntr(USF)=0,0
Exp/Cntr=0.5,0.3

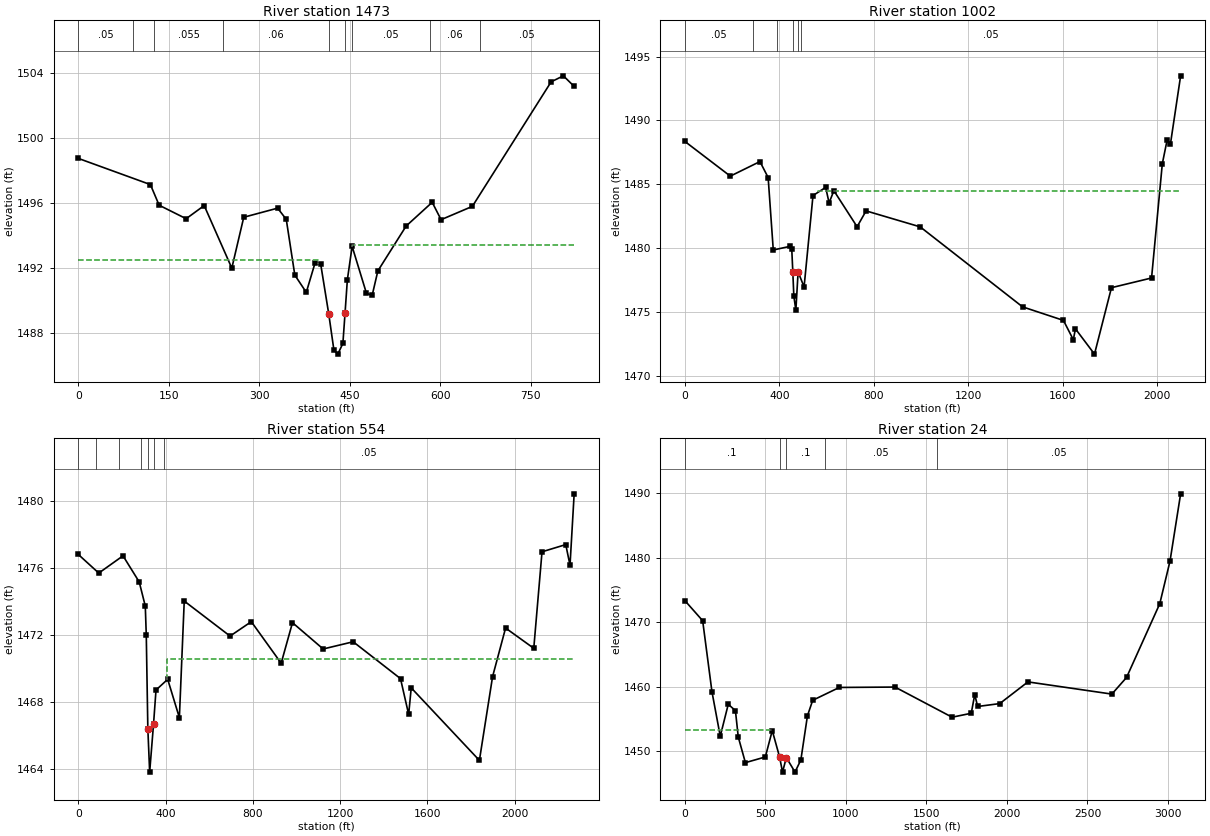
Type RM Length L Ch R = 1 ,1473    ,465.6,471.3,471.7
XS GIS Cut Line= 4
2487109.15858724 617362.908099462487018.37551515617524.909342289
2487234.75530259617863.0027601622487360.97684526618061.350898647
#Sta/Elev= 30
       0 1498.73   119.5 1497.12     134 1495.85   178.8 1495.02   208.7 1495.83
   254.5 1491.98   274.3 1495.11   330.5 1495.67   344.8 1494.98     359 1491.55
     378 1490.49   392.3 1492.27   401.8 1492.25 415.2821489.153   423.8 1486.94
   430.3 1486.69   438.7 1487.35 442.2341489.191   446.1 1491.26     454 1493.32
   477.7 1490.44   487.2  1490.3   496.7 1491.81   543.6 1494.57   586.8 1496.03
   601.5 1494.96   653.4 1495.78     784 1503.44   804.3 1503.81   822.2 1503.16
#Mann= 9 ,-1 , 0
       0     .05       0   91.15     .06       0   125.1    .055       0
  240.17     .06       0 415.282    .045       0 442.234     .06       0
  453.35     .05       0  583.73     .06       0  666.45     .05       0
#XS Ineff= 2 , 0
          397.96 1492.49  454.49         1493.39
Permanent Ineff=
       F       F
Bank Sta=415.282,442.234
XS Rating Curve= 0 ,0
Exp/Cntr(USF)=0,0
Exp/Cntr=0.5,0.3

Type RM Length L Ch R = 1 ,1002    ,447.1,447.9,446.3
XS GIS Cut Line= 4
2486727.89873531617451.5589231032486662.25044832  617655.6387972
2486842.56693786618079.3825476012487477.31066274 619353.35935852
#Sta/Elev= 30
       0 1488.36   192.6 1485.64     318 1486.78   352.7 1485.53   374.4 1479.86
   446.6 1480.15   452.7 1479.91 457.0031478.176   461.4 1476.25     470 1475.15
 479.4881478.138   504.8 1476.97   542.5 1484.12   596.1 1484.76   610.6 1483.55
   630.9  1484.5   729.1 1481.68   767.1 1482.92   996.1 1481.67  1429.3 1475.41
  1602.3 1474.35  1644.1 1472.84  1653.1 1473.69  1733.7 1471.71  1805.5 1476.91
  1975.2 1477.67  2020.7 1486.61  2040.8 1488.44  2055.3 1488.18  2098.2 1493.49
#Mann= 6 ,-1 , 0
       0     .05       0  289.51     .06       0  390.13      .1       0
 457.003    .045       0 479.488      .1       0  490.75     .05       0
#XS Ineff= 2 , 0
                          565.29         1484.48
Permanent Ineff=
       F       F
Bank Sta=457.003,479.488
XS Rating Curve= 0 ,0
Exp/Cntr(USF)=0,0
Exp/Cntr=0.3,0.1

Type RM Length L Ch R = 1 ,554     ,513.9,530.1,551
XS GIS Cut Line= 4
2486328.39109094617807.7121516512486290.84547596617906.622530984
2486526.25867062618382.4577116942487392.77957865619769.892922817
#Sta/Elev= 30
       0 1476.82    93.7 1475.71   204.8 1476.74   279.1 1475.18   306.9 1473.74
   311.4    1472 318.5921466.417   326.9 1463.83 344.7741466.712     356 1468.73
   409.6 1469.37   463.1 1467.08   485.4 1474.04   695.4 1471.95   792.8 1472.81
   929.6 1470.33   981.5 1472.75  1122.1 1471.18  1259.7 1471.61  1476.6 1469.41
    1514 1467.27  1525.7 1468.86  1838.2 1464.53  1898.6 1469.53  1958.2 1472.43
  2087.4 1471.22  2125.2 1476.98    2234 1477.41  2253.5 1476.18  2272.5 1480.44
#Mann= 7 ,-1 , 0
       0     .05       0   82.02    .055       0  186.39     .05       0
  288.66      .1       0 318.592    .045       0 344.774      .1       0
  390.92     .05       0
#XS Ineff= 2 , 0
                           405.6         1470.59
Permanent Ineff=
       F       F
Bank Sta=318.592,344.774
XS Rating Curve= 0 ,0
Exp/Cntr(USF)=0,0
Exp/Cntr=0.3,0.1

Type RM Length L Ch R = 1 ,24      ,,,
XS GIS Cut Line= 5
2486219.64610662617868.9492367042486099.04261975617994.335586223
2486003.48389705618351.3179004372485886.36130476618566.929945343
2487386.46588693620296.682137491
#Sta/Elev= 30
       0 1473.38   110.9 1470.25   168.6 1459.25   220.1 1452.35   269.8  1457.3
   314.3 1456.32   331.9 1452.24   376.2 1448.26     500 1449.14   543.1 1453.23
 588.5591449.128   606.8 1446.79 630.3081449.048   684.2  1446.8   720.6 1448.68
   761.5 1455.52   794.1 1457.92   959.3 1459.91  1305.2 1459.97  1659.7  1455.3
  1778.5 1455.91  1800.1  1458.8  1818.4 1456.96  1955.6 1457.41  2130.4 1460.77
  2651.6 1458.88  2742.8 1461.46  2949.1 1472.89  3012.6 1479.49  3078.5 1489.91
#Mann= 5 ,-1 , 0
       0      .1       0 588.559    .045       0 630.308      .1       0
  873.46     .05       0 1564.32     .05       0
#XS Ineff= 2 , 0
          540.14 1453.38
Permanent Ineff=
       F       F
Bank Sta=588.559,630.308
XS Rating Curve= 0 ,0
Exp/Cntr(USF)=0,0
Exp/Cntr=0.3,0.1
LCMann Table=0

Chan Stop Cuts=-1
Use User Specified Reach Order=0
Composite Channel Slope=5